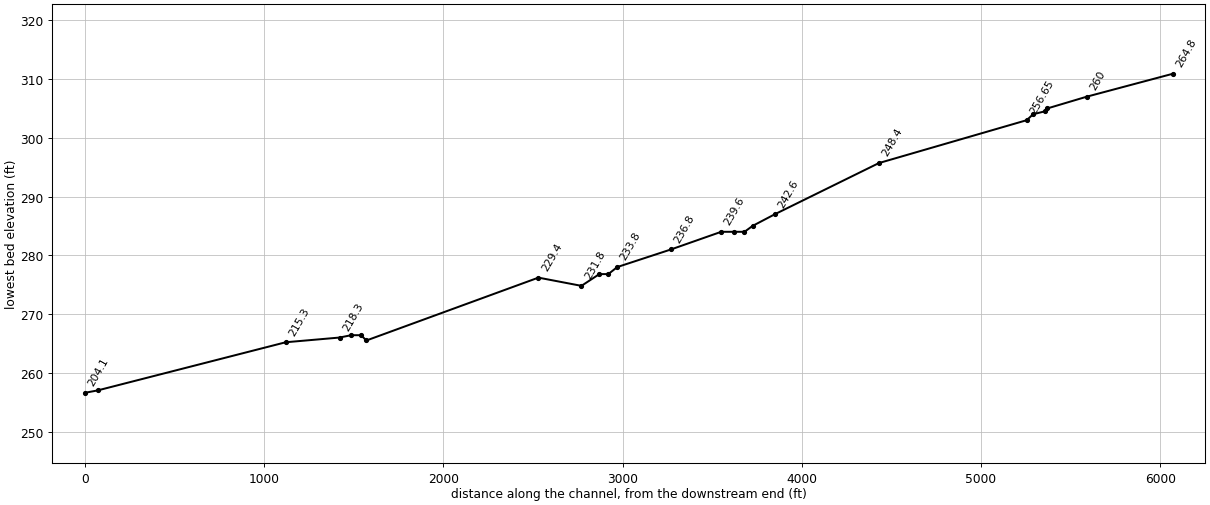
--- CCR_Stoop.prj (project) ---

Proj Title=CCR_Stoop
Current Flow=f02
Default Exp/Contr=0.3,0.1
English Units
Geom File=g01
Geom File=g03
Geom File=g02
Flow File=f01
Flow File=f02
Flow File=f03
Plan File=p01
Plan File=p02
Plan File=p10
Y Axis Title=Elevation
X Axis Title(PF)=Main Channel Distance
X Axis Title(XS)=Station
BEGIN DESCRIPTION:
Carolina Crossroads: Stoop Creek   RICHLAND COUNTY FIS (RE-STUDY)                    DECEMBER 1988
   STOOP CREEK                                Rev'd   MARCH 1991   cah
   10-YEAR FLOOD
END DESCRIPTION:
DSS File=l:\F&H\Drainage\Carolina Crossroads Hydro\HEC-RAS\Stoops Creek\CCR_Stoop.dss
DSS Export Rating Curves= 0
DSS Export Rating Curve Sorted= 0
DSS Export Volume Flow Curves= 0
DXF Filename=l:\F&H\Drainage\Carolina Crossroads Hydro\HEC-RAS\Stoops Creek\CCR_Stoop.
DXF OffsetX= 0
DXF OffsetY= 0
DXF ScaleX= 1
DXF ScaleY= 10

--- CCR_Stoop.p01 (plan) ---

Plan Title=Imported Plan 01
Program Version=4.10
Short Identifier=Imported Pla
Geom File=g01
Flow File=f01
Subcritical Flow
K Sum by GR= 0
Std Step Tol= 0.01
Critical Tol= 0.01
Num of Std Step Trials= 20
Max Error Tol= 0.3
Flow Tol Ratio= 0.001
Split Flow NTrial= 30
Split Flow Tol= 0.02
Split Flow Ratio= 0.02
Log Output Level= 0
Friction Slope Method= 1
Unsteady Friction Slope Method= 2
Unsteady Bridges Friction Slope Method= 1
Parabolic Critical Depth
Global Vel Dist= 0 , 0 , 0
Global Log Level= 0
CheckData=True
Encroach Param=-1 ,0,0, 4
Encroach River=RIVER-1
Encroach Reach=Reach-1
Encroach Node=4.9
       0       0       0       0       0       0       0       0       0
Encroach Node=8.05
       0       0       0       0       0       0       0       0       0
Encroach Node=12.5
       0       0       0       0       0       0       0       0       0
Encroach Node=14.9
       0       0       0       0       0       0       0       0       0
Encroach Node=15.35
       0       0       0       0       0       0       0       0       0
Encroach Node=15.8
       0                       0                       0
Encroach Node=16.25
       0       0       0       0       0       0       0       0       0
Encroach Node=16.7
       0       0       0       0       0       0       0       0       0
Encroach Node=20.6
       0       0       0       0       0       0       0       0       0
Encroach Node=24.55
       0       0       0       0       0       0       0       0       0
Encroach Node=24.85
       0       0       0       0       0       0       0       0       0
Encroach Node=25.3
       0                       0                       0
Encroach Node=25.75
       0       0       0       0       0       0       0       0       0
Encroach Node=26.25
       0       0       0       0       0       0       0       0       0
Encroach Node=35.4
       0       0       0       0       0       0       0       0       0
Encroach Node=41.8
       0       0       0       0       0       0       0       0       0
Encroach Node=42.5
       0       0       0       0       0       0       0       0       0
Encroach Node=43
       0       0       0       0       0       0       0       0       0
Encroach Node=46.6
       0       0       0       0       0       0       0       0       0
Encroach Node=48.6
       0                       0                       0
Encroach Node=50.6
       0       0       0       0       0       0       0       0       0
Encroach Node=51.1
       0       0       0       0       0       0       0       0       0
Encroach Node=53.3
       0       0       0       0       0       0       0       0       0
Encroach Node=56.8
       0       0       0       0       0       0       0       0       0
Encroach Node=61.2
       0       0       0       0       0       0       0       0       0
Encroach Node=61.7
       0       0       0       0       0       0       0       0       0
Encroach Node=62.1
       0                       0                       0
Encroach Node=62.5
       0       0       0       0       0       0       0       0       0
Encroach Node=63.4
       0       0       0       0       0       0       0       0       0
Encroach Node=71.3
       0       0       0       0       0       0       0       0       0
Encroach Node=78.8
       0       0       0       0       0       0       0       0       0
Encroach Node=80
       0       0       0       0       0       0       0       0       0
Encroach Node=84.9
       0                       0                       0
Encroach Node=89.8
       0       0       0       0       0       0       0       0       0
Encroach Node=90.3
       0       0       0       0       0       0       0       0       0
Encroach Node=91.3
       0       0       0       0       0       0       0       0       0
Encroach Node=93.3
       0       0       0       0       0       0       0       0       0
Encroach Node=94.6
       0       0       0       0       0       0       0       0       0
Encroach Node=94.8
       0       0       0       0       0       0       0       0       0
Encroach Node=95.2
       0       0       0       0       0       0       0       0       0
Encroach Node=95.35
       0       0       0       0       0       0       0       0       0
Encroach Node=97.3
       0       0       0       0       0       0       0       0       0
Encroach Node=97.9
       0       0       0       0       0       0       0       0       0
Encroach Node=98.10001
       0                       0                       0
Encroach Node=98.3
       0       0       0       0       0       0       0       0       0
Encroach Node=98.9
       0       0       0       0       0       0       0       0       0
Encroach Node=101.8
       0       0       0       0       0       0       0       0       0
Encroach Node=104
       0       0       0       0       0       0       0       0       0
Encroach Node=105.75
       0       0       0       0       0       0       0       0       0
Encroach Node=110
       0       0       0       0       0       0       0       0       0
Encroach Node=118.55
       0       0       0       0       0       0       0       0       0
Encroach Node=119.35
       0       0       0       0       0       0       0       0       0
Encroach Node=120.075
       0                       0                       0
Encroach Node=120.8
       0       0       0       0       0       0       0       0       0
Encroach Node=121
       0       0       0       0       0       0       0       0       0
Encroach Node=123.15
       0       0       0       0       0       0       0       0       0
Encroach Node=126.45
       0       0       0       0       0       0       0       0       0
Encroach Node=126.65
       0       0       0       0       0       0       0       0       0
Encroach Node=126.975
       0                       0                       0
Encroach Node=127.3
       0       0       0       0       0       0       0       0       0
Encroach Node=127.7
       0       0       0       0       0       0       0       0       0
Encroach Node=130.9
       0       0       0       0       0       0       0       0       0
Encroach Node=137.8
       0       0       0       0       0       0       0       0       0
Encroach Node=145.05
       0       0       0       0       0       0       0       0       0
Encroach Node=149.4
       0       0       0       0       0       0       0       0       0
Encroach Node=155.6
       0       0       0       0       0       0       0       0       0
Encroach Node=155.8
       0       0       0       0       0       0       0       0       0
Encroach Node=156.3
       0                       0                       0
Encroach Node=156.8
       0       0       0       0       0       0       0       0       0
Encroach Node=157.3
       0       0       0       0       0       0       0       0       0
Encroach Node=162.3
       0       0       0       0       0       0       0       0       0
Encroach Node=168.8
       0       0       0       0       0       0       0       0       0
Encroach Node=173.8
       0       0       0       0       0       0       0       0       0
Encroach Node=179
       0       0       0       0       0       0       0       0       0
Encroach Node=179.5
       0       0       0       0       0       0       0       0       0
Encroach Node=180
       0                       0                       0
Encroach Node=180.5
       0       0       0       0       0       0       0       0       0
Encroach Node=180.7
       0       0       0       0       0       0       0       0       0
Encroach Node=193.05
       0       0       0       0       0       0       0       0       0
Encroach Node=193.7
       0       0       0       0       0       0       0       0       0
Encroach Node=194.05
       0                       0                       0
Encroach Node=194.4
       0       0       0       0       0       0       0       0       0
Encroach Node=194.8
       0       0       0       0       0       0       0       0       0
Encroach Node=198.7
       0       0       0       0       0       0       0       0       0
Encroach Node=201.8
       0       0       0       0       0       0       0       0       0
Encroach Node=202.3
       0       0       0       0       0       0       0       0       0
Encroach Node=202.475
       0                       0                       0
Encroach Node=202.65
       0       0       0       0       0       0       0       0       0
Encroach Node=202.8
       0       0       0       0       0       0       0       0       0
Encroach Node=202.95
       0       0       0       0       0       0       0       0       0
Encroach Node=203.1
       0       0       0       0       0       0       0       0       0
Encroach Node=203.6
       0                       0                       0
Encroach Node=204.1
       0       0       0       0       0       0       0       0       0
Encroach Node=204.8
       0       0       0       0       0       0       0       0       0
Encroach Node=215.3
       0       0       0       0       0       0       0       0       0
Encroach Node=218.3
       0       0       0       0       0       0       0       0       0
Encroach Node=218.95
       0       0       0       0       0       0       0       0       0
Encroach Node=219.225
       0                       0                       0
Encroach Node=219.5
       0       0       0       0       0       0       0       0       0
Encroach Node=219.8
       0       0       0       0       0       0       0       0       0
Encroach Node=229.4
       0       0       0       0       0       0       0       0       0
Encroach Node=231.8
       0       0       0       0       0       0       0       0       0
Encroach Node=232.8
       0       0       0       0       0       0       0       0       0
Encroach Node=233.05
       0                       0                       0
Encroach Node=233.3
       0       0       0       0       0       0       0       0       0
Encroach Node=233.8
       0       0       0       0       0       0       0       0       0
Encroach Node=236.8
       0       0       0       0       0       0       0       0       0
Encroach Node=239.6
       0       0       0       0       0       0       0       0       0
Encroach Node=240.3
       0       0       0       0       0       0       0       0       0
Encroach Node=240.6
       0                       0                       0
Encroach Node=240.9
       0       0       0       0       0       0       0       0       0
Encroach Node=241.35
       0       0       0       0       0       0       0       0       0
Encroach Node=242.6
       0       0       0       0       0       0       0       0       0
Encroach Node=248.4
       0       0       0       0       0       0       0       0       0
Encroach Node=256.65
       0       0       0       0       0       0       0       0       0
Encroach Node=257
       0       0       0       0       0       0       0       0       0
Encroach Node=257.325
       0                       0                       0
Encroach Node=257.65
       0       0       0       0       0       0       0       0       0
Encroach Node=257.8
       0       0       0       0       0       0       0       0       0
Encroach Node=260
       0       0       0       0       0       0       0       0       0
Encroach Node=264.8
       0       0       0       0       0       0       0       0       0
Computation Interval=1HOUR
Output Interval=1HOUR
Run HTab= 0
Run UNet= 0
Run PostProcess= 0
Run WQNet= 0
UNET Theta= 1
UNET Theta Warmup= 1
UNET ZTol= 0.02
UNET ZSATol= 0.05
UNET MxIter= 20
UNET MaxInSteps= 0
UNET DtIC= 0
UNET DtMin= 0
UNET MaxCRTS= 20
UNET WFStab= 2
UNET SFStab= 1
UNET WFX= 1
UNET SFX= 1
UNET DSS MLevel= 4
UNET DZMax Abort= 100
UNET Convert EG Bridges= 0
UNET Use Existing IB Tables=-1
UNET Froude Reduction=False
UNET Froude Limit= 1
UNET Froude Power= 10
UNET Time Slicing=0,0, 5
UNET Junction Losses=0
Instantaneous Interval=1HOUR
DSS File=dss
Write IC File= 0
Write IC File at Sim End=0
Echo Input=False
Echo Parameters=False
Echo Output=False
Write Detailed= 0
WQ AD Non Conservative
WQ ULTIMATE=-1
WQ Max Comp Step=1HOUR
WQ Output Interval=15MIN
WQ Output Selected Increments= 0
WQ Output face flow=0
WQ Output face velocity=0
WQ Output face area=0
WQ Output face dispersion=0
WQ Output cell volume=0
WQ Output cell surface area=0
WQ Output cell continuity=0
WQ Output cumulative cell continuity=0
WQ Output face conc=0
WQ Output face dconc_dx=0
WQ Output face courant=0
WQ Output face peclet=0
WQ Output face adv mass=0
WQ Output face disp mass=0
WQ Output cell mass=0
WQ Output cell source sink temp=0
WQ Output cell source sink nsm=0
WQ Output MaxMinRange=-1
WQ Daily Max Min Mean=-1
WQ Daily Range=0
WQ Daily Time=0
WQ Create Restart=0
WQ Fixed Restart=0
WQ System Summary=0
WQ Use Fixed Temperature=0
Sorting and Armoring Iterations= 10
XS Update Threshold= 0.02
Hydraulics Update Threshold= 0.02
Energy Slope Method= 1
Volume Change Method= 0
XS Weighting Method= 0
Number of US Weighted Cross Sections= 1
Number of DS Weighted Cross Sections= 1
Upstream XS Weight=0.25
Main XS Weight=0.5
Downstream XS Weight=0.25
Number of DS XS's Weighted with US Boundary= 1
Upstream Boundary Weight= 1
Weight of XSs Associated with US Boundary= 0
Number of US XS's Weighted with DS Boundary= 1
Downstream Boundary Weight= 0.5
Weight of XSs Associated with DS Boundary= 0.5
Sediment Output Level= 4
Mass or Volume Output= 0
Output Increment Type= 1
Profile and TS Output Increment= 10
XS Output Flag= 0
XS Output Increment= 10
Disregard all LS=0
Disregard all Conn=0
Disregard all Breaches=0
Disregard all Pumps=0

--- CCR_Stoop.p02 (plan) ---

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Plan Title=Corrected
Short Identifier=Corrected
Geom File=g03
Flow File=f02

--- CCR_Stoop.p10 (plan) ---

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Plan Title=Natural
Short Identifier=Natural
Geom File=g02
Flow File=f02

--- CCR_Stoop.f01 (steady flow) ---

Flow Title=Imported Flow 01
Program Version=4.10
Number of Profiles= 1
Profile Names=100-yr
River Rch & RM=Stoop Creek,Stoop Creek     ,264.8
     356
River Rch & RM=Stoop Creek,Stoop Creek     ,204.1
     321
River Rch & RM=Stoop Creek,Stoop Creek     ,180.5
     616
River Rch & RM=Stoop Creek,Stoop Creek     ,120.8
    2210
River Rch & RM=Stoop Creek,Stoop Creek     ,90.3
    3525
River Rch & RM=Stoop Creek,Stoop Creek     ,71.3
    2831
River Rch & RM=Stoop Creek,Stoop Creek     ,51.1
    3483
River Rch & RM=Stoop Creek,Stoop Creek     ,42.5
    2213
River Rch & RM=Stoop Creek,Stoop Creek     ,4.9
    2203
Boundary for River Rch & Prof#=Stoop Creek,Stoop Creek     , 1
Up Type= 0
Dn Type= 3
Dn Slope=0.0016
DSS Import GetInterval= 0
DSS Import GetPeak= 0
DSS Import FillOption= 0

--- CCR_Stoop.f02 (steady flow) ---

Flow Title=Updated Flows
Program Version=4.10
Number of Profiles= 5
Profile Names=10 year,25 Year,50 Year,100 Year,500 Year
River Rch & RM=Stoop Creek,Stoop Creek     ,264.8
     285     374     451     535     627
River Rch & RM=Stoop Creek,Stoop Creek     ,201.8
     386     512     620     739    1057
River Rch & RM=Stoop Creek,Stoop Creek     ,180.7
     635     838     991    1142    1774
River Rch & RM=Stoop Creek,Stoop Creek     ,168.8
     807    1105    1332    1581    2106
River Rch & RM=Stoop Creek,Stoop Creek     ,145.05
    1115    1553    1911    2291    3151
River Rch & RM=Stoop Creek,Stoop Creek     ,110
    1329    1708    2179    2665    3648
River Rch & RM=Stoop Creek,Stoop Creek     ,90.3
    1862    2422    2875    3369    4787
River Rch & RM=Stoop Creek,Stoop Creek     ,71.3
    1699    2137    2450    2831    3763
River Rch & RM=Stoop Creek,Stoop Creek     ,51.1
    2115    2635    2995    3483    4664
River Rch & RM=Stoop Creek,Stoop Creek     ,42.5
    1579    1785    1893    2213    3767
River Rch & RM=Stoop Creek,Stoop Creek     ,4.9
    1642    1843    1973    2203    3141
Boundary for River Rch & Prof#=Stoop Creek,Stoop Creek     , 1
Up Type= 0
Dn Type= 3
Dn Slope=0.0016
DSS Import GetInterval= 0
DSS Import GetPeak= 0
DSS Import FillOption= 0

--- CCR_Stoop.f03 (steady flow) ---

Flow Title=Imported Flow 01_KnownWSE
Program Version=4.10
Number of Profiles= 1
Profile Names=100-yr
River Rch & RM=Stoop Creek,Stoop Creek     ,264.8
     356
River Rch & RM=Stoop Creek,Stoop Creek     ,204.1
     321
River Rch & RM=Stoop Creek,Stoop Creek     ,180.5
     616
River Rch & RM=Stoop Creek,Stoop Creek     ,120.8
    2210
River Rch & RM=Stoop Creek,Stoop Creek     ,90.3
    3525
River Rch & RM=Stoop Creek,Stoop Creek     ,71.3
    2831
River Rch & RM=Stoop Creek,Stoop Creek     ,51.1
    3483
River Rch & RM=Stoop Creek,Stoop Creek     ,42.5
    2213
River Rch & RM=Stoop Creek,Stoop Creek     ,4.9
    2203
Boundary for River Rch & Prof#=Stoop Creek,Stoop Creek     , 1
Up Type= 0
Dn Type= 1
Dn Known WS=169.49
DSS Import GetInterval= 0
DSS Import GetPeak= 0
DSS Import FillOption= 0

--- CCR_Stoop.g01 (geometry) ---

Geom Title=Duplicate Effective
Program Version=4.10
BEGIN GEOM DESCRIPTION:
Geometry Imported from HEC-2 data.  No changes/corrections made.
END GEOM DESCRIPTION:

River Reach=Stoop Creek     ,Stoop Creek
Reach XY= 2
             0.5            0.95             0.5            0.05

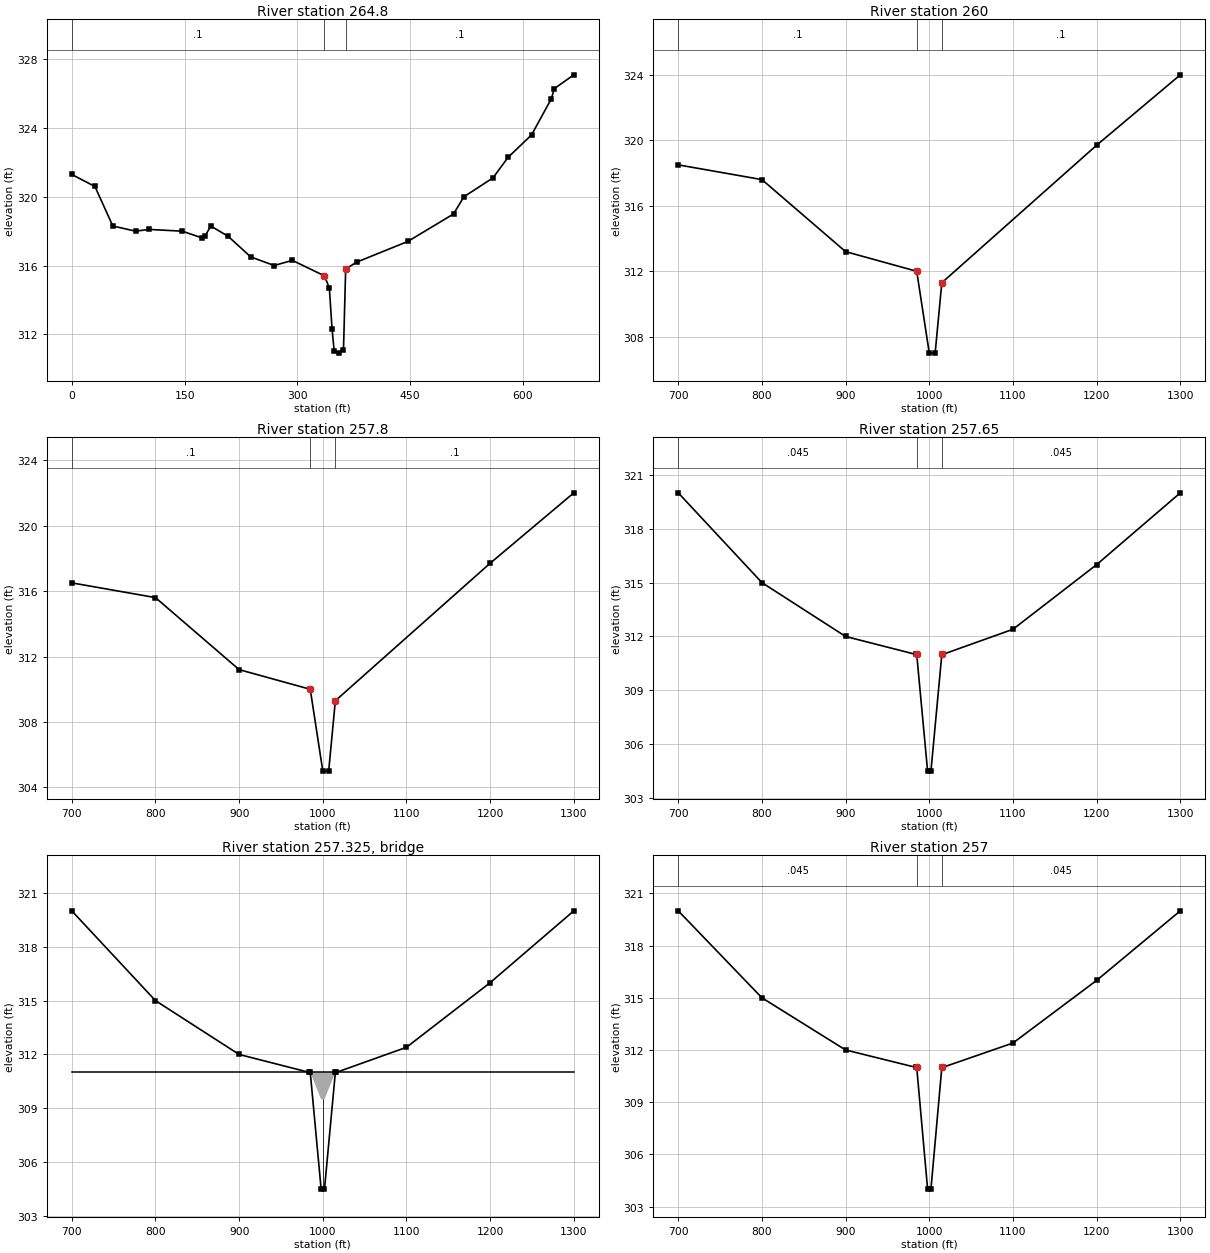
Type RM Length L Ch R = 1 ,264.8   ,480,480,480
#Sta/Elev= 30
       0   321.3    30.8   320.6    54.6   318.3    84.8     318   102.9   318.1
   146.8     318   173.7   317.6   177.1   317.7   184.8   318.3   207.9   317.7
     238   316.5   269.1     316   293.3   316.3   335.9   315.4   342.5   314.7
   346.1   312.3     349     311   355.1   310.9   361.3   311.1   364.2   315.8
     379   316.2   446.8   317.4   507.6     319   521.4     320     560   321.1
   580.2   322.3   611.3   323.6   637.6   325.7   641.7   326.3   667.6   327.1
#Mann= 3 , 0 , 0
       0      .1       0   335.9     .06       0   364.2      .1       0
Bank Sta=335.9,364.2
XS Rating Curve= 0 ,0
Exp/Cntr=0.3,0.1

Type RM Length L Ch R = 1 ,260     ,220,220,220
#Sta/Elev= 9
     700   318.5     800   317.6     900   313.2     985     312    1000     307
    1007     307    1015   311.3    1200   319.7    1300     324
#Mann= 3 , 0 , 0
     700      .1       0     985     .06       0    1015      .1       0
Bank Sta=985,1015
XS Rating Curve= 0 ,0
Exp/Cntr=0.3,0.1

Type RM Length L Ch R = 1 ,257.8   ,15,15,15
BEGIN DESCRIPTION:
RICH CNTY FEMA XS: AD
END DESCRIPTION:
#Sta/Elev= 9
     700   316.5     800   315.6     900   311.2     985     310    1000     305
    1007     305    1015   309.3    1200   317.7    1300     322
#Mann= 3 , 0 , 0
     700      .1       0     985     .06       0    1015      .1       0
Bank Sta=985,1015
XS Rating Curve= 0 ,0
Exp/Cntr=0.3,0.1

Type RM Length L Ch R = 1 ,257.65  ,65,65,65
#Sta/Elev= 12
     700     320     800     315     900     312     984     311     985     311
     998   304.5    1002   304.5    1015     311    1016     311    1100   312.4
    1200     316    1300     320
#Mann= 3 , 0 , 0
     700    .045       0     985   .0315       0    1015    .045       0
#XS Ineff= 2 , 0
             985     311    1015             311
Permanent Ineff=
       F       F
Bank Sta=985,1015
XS Rating Curve= 0 ,0
Exp/Cntr=0.5,0.3

Type RM Length L Ch R = 3 ,257.325 ,,,
BEGIN DESCRIPTION:
Bridge #17
END DESCRIPTION:
Bridge Culvert--1,0,-1,-1, 0
Deck Dist Width WeirC Skew NumUp NumDn MinLoCord MaxHiCord MaxSubmerge Is_Ogee
0.25,64.5,2.6,0, 6, 6, 311, , 0.98, 0, 0,0,,
     700     985     985    1015    1015    1300
     311     311     311     311     311     311
     304     304   309.5   309.5     304     304
     700     985     985    1015    1015    1300
     311     311     311     311     311     311
     304     304   309.5   309.5     304     304
Pier Skew, UpSta & Num, DnSta & Num=  ,1000, 2 ,1000, 2 , 0 , 0 , 0 ,,
      .1      .1
   304.5   309.5
      .1      .1
     304   309.5
BR Coef= 0 , 0 ,-1 ,0.9, 0 ,,,0.8006408,0,,2,309.5
WSPro=,,,, 1 ,,,, 0 ,,,, 0 ,,,,-1 ,-1 ,-1 , 0 , 0 , 0 , 0 , 0
BC Design=,, 0 ,, 0 ,,,,,,
BC Use User HTab Curves=0
BC User HTab FreeFlow(D)= 0

Type RM Length L Ch R = 1 ,257     ,35,35,35
#Sta/Elev= 12
     700     320     800     315     900     312     984     311     985     311
     998     304    1002     304    1015     311    1016     311    1100   312.4
    1200     316    1300     320
#Mann= 3 , 0 , 0
     700    .045       0     985   .0315       0    1015    .045       0
#XS Ineff= 2 , 0
             985   309.5    1015           309.5
Permanent Ineff=
       F       F
Bank Sta=985,1015
XS Rating Curve= 0 ,0
Exp/Cntr=0.5,0.3

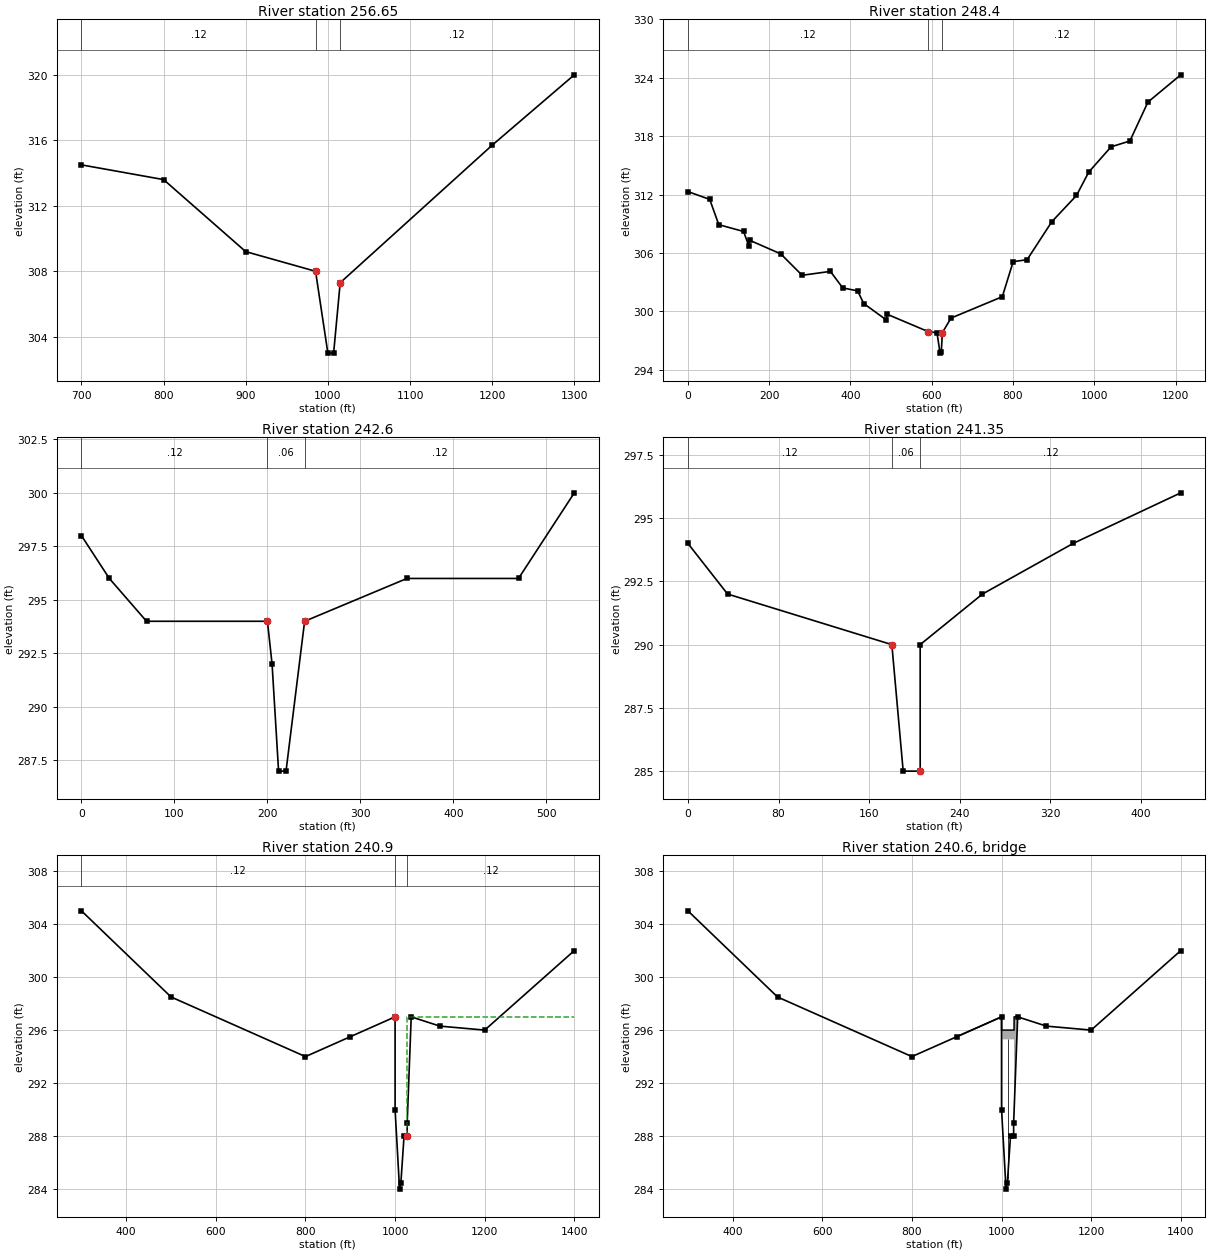
Type RM Length L Ch R = 1 ,256.65  ,825,825,825
BEGIN DESCRIPTION:
RICH CNTY FEMA XS: AC
END DESCRIPTION:
#Sta/Elev= 9
     700   314.5     800   313.6     900   309.2     985     308    1000     303
    1007     303    1015   307.3    1200   315.7    1300     320
#Mann= 3 , 0 , 0
     700     .12       0     985     .06       0    1015     .12       0
Bank Sta=985,1015
XS Rating Curve= 0 ,0
Exp/Cntr=0.3,0.1

Type RM Length L Ch R = 1 ,248.4   ,580,580,580
BEGIN DESCRIPTION:
RICH CNTY FEMA XS: AB
END DESCRIPTION:
#Sta/Elev= 30
       0   312.3    53.7   311.5      76   308.9   137.1   308.2   149.9   306.7
   151.8   307.3   228.4   305.9     281   303.7   350.6   304.1     381   302.4
   417.6   302.1   432.5   300.8   488.6   299.1   489.9   299.7   591.8   297.9
   612.8   297.8   620.6   295.7   623.5   295.8   626.1   297.8   647.3   299.3
   773.6   301.5   800.3   305.1   834.6   305.3   895.3   309.2   956.1   311.9
   986.2   314.3  1041.2   316.9  1087.5   317.5  1131.9   321.5  1212.7   324.3
#Mann= 3 , 0 , 0
       0     .12       0   591.8     .06       0   626.1     .12       0
Bank Sta=591.8,626.1
XS Rating Curve= 0 ,0
Exp/Cntr=0.3,0.1

Type RM Length L Ch R = 1 ,242.6   ,125,125,125
#Sta/Elev= 11
       0     298      30     296      70     294     200     294     205     292
     212     287     220     287     240     294     350     296     470     296
     530     300
#Mann= 3 , 0 , 0
       0     .12       0     200     .06       0     240     .12       0
Bank Sta=200,240
XS Rating Curve= 0 ,0
Exp/Cntr=0.3,0.1

Type RM Length L Ch R = 1 ,241.35  ,45,45,45
BEGIN DESCRIPTION:
RICH CNTY FEMA XS: AA
END DESCRIPTION:
#Sta/Elev= 9
       0     294      35     292     180     290     190     285     205     285
     205     290     260     292     340     294     435     296
#Mann= 3 , 0 , 0
       0     .12       0     180     .06       0     205     .12       0
Bank Sta=180,205
XS Rating Curve= 0 ,0
Exp/Cntr=0.3,0.1

Type RM Length L Ch R = 1 ,240.9   ,60,60,60
#Sta/Elev= 15
     300     305     500   298.5     800     294     900   295.5    1000     297
    1000     290    1010     284    1013   284.5    1020     288    1027     288
    1027     289    1036     297    1100   296.3    1200     296    1400     302
#Mann= 3 , 0 , 0
     300     .12       0    1000     .06       0    1027     .12       0
#XS Ineff= 2 , 0
            1000     297    1027             297
Permanent Ineff=
       F       F
Bank Sta=1000,1027
XS Rating Curve= 0 ,0
Exp/Cntr=0.3,0.1

Type RM Length L Ch R = 3 ,240.6   ,,,
BEGIN DESCRIPTION:
Bridge #16
END DESCRIPTION:
Bridge Culvert--1,0,-1,-1, 0
Deck Dist Width WeirC Skew NumUp NumDn MinLoCord MaxHiCord MaxSubmerge Is_Ogee
0.25,59.5,2.6,0, 6, 6, 297, , 0.98, 0, 0,0,,
     900    1000  1000.1  1027.9    1028    1036
   295.5     297     296     296     297     297
       0       0   295.3   295.3       0       0
     900    1000  1000.1  1027.9    1028    1036
   295.5     297     296     296     297     297
       0       0   295.3   295.3       0       0
Pier Skew, UpSta & Num, DnSta & Num=  ,1013.5, 2 ,1013.5, 2 , 0 , 0 , 0 ,,
      .1      .1
     284   295.3
      .1      .1
     284   295.3
BR Coef= 0 , 0 ,-1 ,0.9, 0 ,,,0.8006408,0,,2,295.3
WSPro=,,,, 1 ,,,, 0 ,,,, 0 ,,,,-1 ,-1 ,-1 , 0 , 0 , 0 , 0 , 0
BC Design=,, 0 ,, 0 ,,,,,,
BC Use User HTab Curves=0
BC User HTab FreeFlow(D)= 0

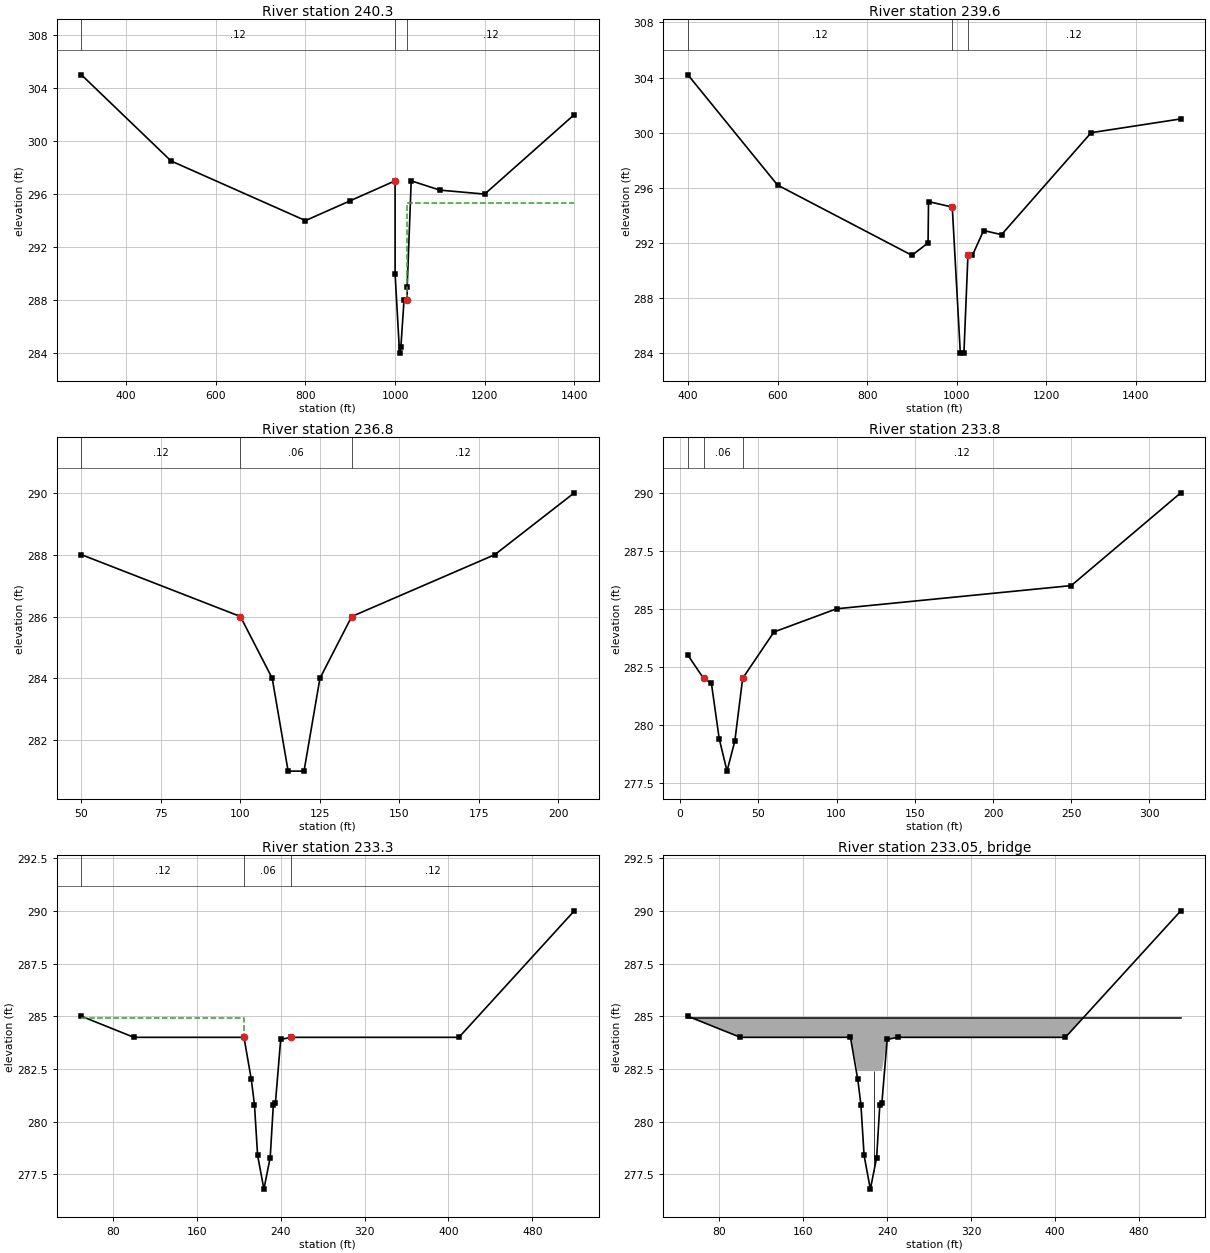
Type RM Length L Ch R = 1 ,240.3   ,70,70,70
BEGIN DESCRIPTION:
RICH CNTY FEMA XS: Z
END DESCRIPTION:
#Sta/Elev= 15
     300     305     500   298.5     800     294     900   295.5    1000     297
    1000     290    1010     284    1013   284.5    1020     288    1027     288
    1027     289    1036     297    1100   296.3    1200     296    1400     302
#Mann= 3 , 0 , 0
     300     .12       0    1000     .06       0    1027     .12       0
#XS Ineff= 2 , 0
            1000   295.3    1027           295.3
Permanent Ineff=
       F       F
Bank Sta=1000,1027
XS Rating Curve= 0 ,0
Exp/Cntr=0.3,0.1

Type RM Length L Ch R = 1 ,239.6   ,280,280,280
#Sta/Elev= 14
     400   304.2     600   296.2     900   291.1     936     292     937     295
     990   294.6    1008     284    1016     284    1025   291.1    1035   291.1
    1060   292.9    1100   292.6    1300     300    1500     301
#Mann= 3 , 0 , 0
     400     .12       0     990     .06       0    1025     .12       0
Bank Sta=990,1025
XS Rating Curve= 0 ,0
Exp/Cntr=0.3,0.1

Type RM Length L Ch R = 1 ,236.8   ,300,300,300
BEGIN DESCRIPTION:
RICH CNTY FEMA XS: Y
END DESCRIPTION:
#Sta/Elev= 9
      50     288     100     286     110     284     115     281     120     281
     125     284     135     286     180     288     205     290
#Mann= 3 , 0 , 0
      50     .12       0     100     .06       0     135     .12       0
Bank Sta=100,135
XS Rating Curve= 0 ,0
Exp/Cntr=0.3,0.1

Type RM Length L Ch R = 1 ,233.8   ,50,50,50
BEGIN DESCRIPTION:
RICH CNTY FEMA XS: X
END DESCRIPTION:
#Sta/Elev= 11
       5     283      15     282      20   281.8      25   279.4      30     278
      35   279.3      40     282      60     284     100     285     250     286
     320     290
#Mann= 3 , 0 , 0
       5     .12       0      15     .06       0      40     .12       0
Bank Sta=15,40
XS Rating Curve= 0 ,0
Exp/Cntr=0.3,0.1

Type RM Length L Ch R = 1 ,233.3   ,50,50,50
#Sta/Elev= 14
      50     285     100     284     205     284     212     282     215   280.8
     218   278.4     224   276.8     230   278.3     233   280.8     235   280.9
     240   283.9     250     284     410     284     520     290
#Mann= 3 , 0 , 0
      50     .12       0     205     .06       0     250     .12       0
#XS Ineff= 2 , 0
             205   284.9     250           282.5
Permanent Ineff=
       F       F
Bank Sta=205,250
XS Rating Curve= 0 ,0
Exp/Cntr=0.3,0.1

Type RM Length L Ch R = 3 ,233.05  ,,,
BEGIN DESCRIPTION:
Bridge #15
END DESCRIPTION:
Bridge Culvert--1,0,-1,-1, 0
Deck Dist Width WeirC Skew NumUp NumDn MinLoCord MaxHiCord MaxSubmerge Is_Ogee
0.25,49.5,2.6,0, 6, 6, 284.9, , 0.98, 0, 0,0,,
      50     205     205     250     250     520
   284.9   284.9   284.9   284.9   284.9   284.9
   276.8   276.8   282.4   282.4   276.8   276.8
      50     300     300     340     340     520
   284.9   284.9   284.9   284.9   284.9   284.9
   276.8   276.8   282.4   282.4   276.8   276.8
Pier Skew, UpSta & Num, DnSta & Num=  ,227.5, 2 ,320, 2 , 0 , 0 , 0 ,,
     .01     .01
   276.8   282.4
     .01     .01
   276.8   282.4
BR Coef= 0 , 0 ,-1 ,0.9, 0 ,,,0.8006408,0,,2,282.4
WSPro=,,,, 1 ,,,, 0 ,,,, 0 ,,,,-1 ,-1 ,-1 , 0 , 0 , 0 , 0 , 0
BC Design=,, 0 ,, 0 ,,,,,,
BC Use User HTab Curves=0
BC User HTab FreeFlow(D)= 0

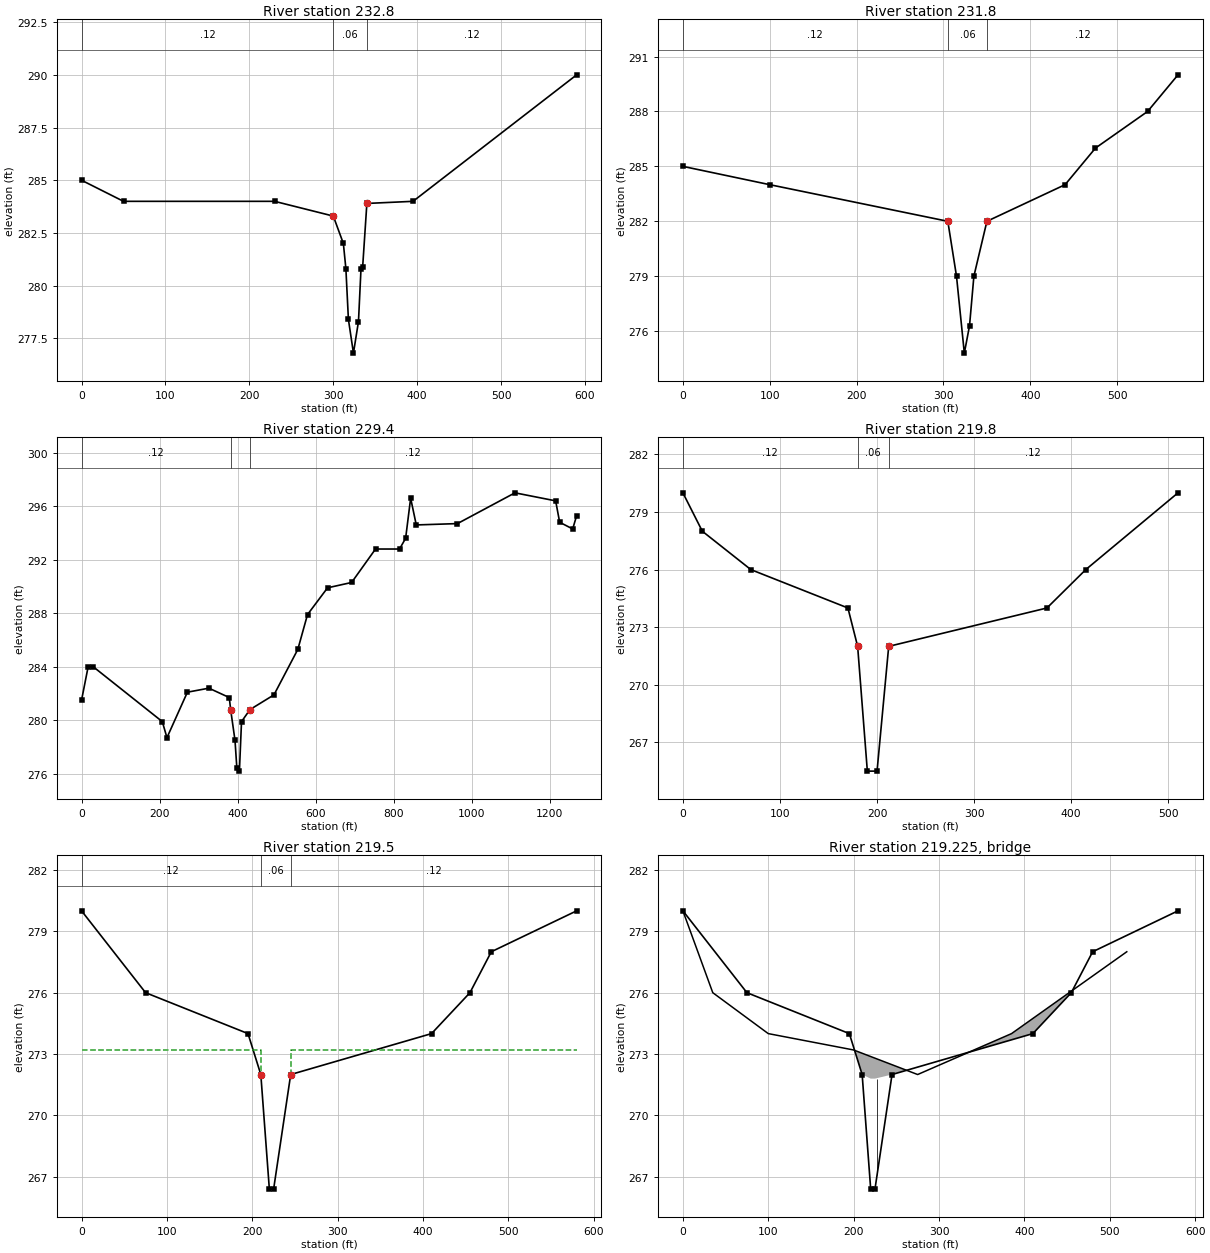
Type RM Length L Ch R = 1 ,232.8   ,100,100,100
#Sta/Elev= 14
       0     285      50     284     230     284     300   283.3     312     282
     315   280.8     318   278.4     324   276.8     330   278.3     333   280.8
     335   280.9     340   283.9     395     284     590     290
#Mann= 3 , 0 , 0
       0     .12       0     300     .06       0     340     .12       0
#XS Ineff= 2 , 0
             300   282.5     340           282.5
Permanent Ineff=
       F       F
Bank Sta=300,340
XS Rating Curve= 0 ,0
Exp/Cntr=0.3,0.1

Type RM Length L Ch R = 1 ,231.8   ,240,240,240
#Sta/Elev= 12
       0     285     100     284     305     282     315     279     324   274.8
     330   276.3     335     279     350     282     440     284     475     286
     535     288     570     290
#Mann= 3 , 0 , 0
       0     .12       0     305     .06       0     350     .12       0
Bank Sta=305,350
XS Rating Curve= 0 ,0
Exp/Cntr=0.3,0.1

Type RM Length L Ch R = 1 ,229.4   ,960,960,960
BEGIN DESCRIPTION:
RICH CNTY FEMA XS: W
END DESCRIPTION:
#Sta/Elev= 30
       0   281.5    16.9     284      30     284   207.1   279.9     219   278.7
   271.4   282.1   326.6   282.4   378.8   281.7   382.3   280.8   393.5   278.5
   398.3   276.4   404.8   276.2   410.2   279.9   431.9   280.8   493.4   281.9
   554.6   285.3   579.4   287.9   630.8   289.9   692.5   290.3   753.8   292.8
   815.4   292.8     831   293.6   843.9   296.6   858.3   294.6   963.9   294.7
  1111.4     297  1215.7   296.4    1226   294.8  1259.4   294.3  1269.6   295.3
#Mann= 3 , 0 , 0
       0     .12       0   382.3     .06       0   431.9     .12       0
Bank Sta=382.3,431.9
XS Rating Curve= 0 ,0
Exp/Cntr=0.3,0.1

Type RM Length L Ch R = 1 ,219.8   ,30,30,30
BEGIN DESCRIPTION:
RICH CNTY FEMA XS: V
END DESCRIPTION:
#Sta/Elev= 11
       0     280      20     278      70     276     170     274     180     272
     190   265.5     200   265.5     212     272     375     274     415     276
     510     280
#Mann= 3 , 0 , 0
       0     .12       0     180     .06       0     212     .12       0
Bank Sta=180,212
XS Rating Curve= 0 ,0
Exp/Cntr=0.3,0.1

Type RM Length L Ch R = 1 ,219.5   ,55,55,55
#Sta/Elev= 11
       0     280      75     276     195     274     210     272     220   266.4
     225   266.4     245     272     410     274     455     276     480     278
     580     280
#Mann= 3 , 0 , 0
       0     .12       0     210     .06       0     245     .12       0
#XS Ineff= 2 , 0
             210   273.2     245           273.2
Permanent Ineff=
       F       F
Bank Sta=210,245
XS Rating Curve= 0 ,0
Exp/Cntr=0.3,0.1

Type RM Length L Ch R = 3 ,219.225 ,,,
BEGIN DESCRIPTION:
Bridge #14
END DESCRIPTION:
Bridge Culvert--1,0,-1,-1, 0
Deck Dist Width WeirC Skew NumUp NumDn MinLoCord MaxHiCord MaxSubmerge Is_Ogee
0.25,54.5,2.6,0, 11, 11, 273.2, , 0.98, 0, 0,0,,
       0      35     100     200     210     210     245     245     275     385
     520
     280     276     274   273.2  273.04  273.04  272.48  272.48     272     274
     278
   266.4   266.4   266.4   266.4   266.4   271.8   271.8   266.4   266.4   266.4
   266.4
       0      35     100     175     175     200     215     215     275     385
     520
     280     276     274   273.4   273.4   273.2  272.96  272.96     272     274
     278
   266.4   266.4   266.4   266.4   271.8   271.8   271.8   266.4   266.4   266.4
   266.4
Pier Skew, UpSta & Num, DnSta & Num=  ,227.5, 2 ,195, 2 , 0 , 0 , 0 ,,
     .01     .01
   266.4   271.8
     .01     .01
   266.4   271.8
BR Coef= 0 , 0 ,-1 ,0.9, 0 ,,,0.8006408,0,,2,271.8
WSPro=,,,, 1 ,,,, 0 ,,,, 0 ,,,,-1 ,-1 ,-1 , 0 , 0 , 0 , 0 , 0
BC Design=,, 0 ,, 0 ,,,,,,
BC Use User HTab Curves=0
BC User HTab FreeFlow(D)= 0

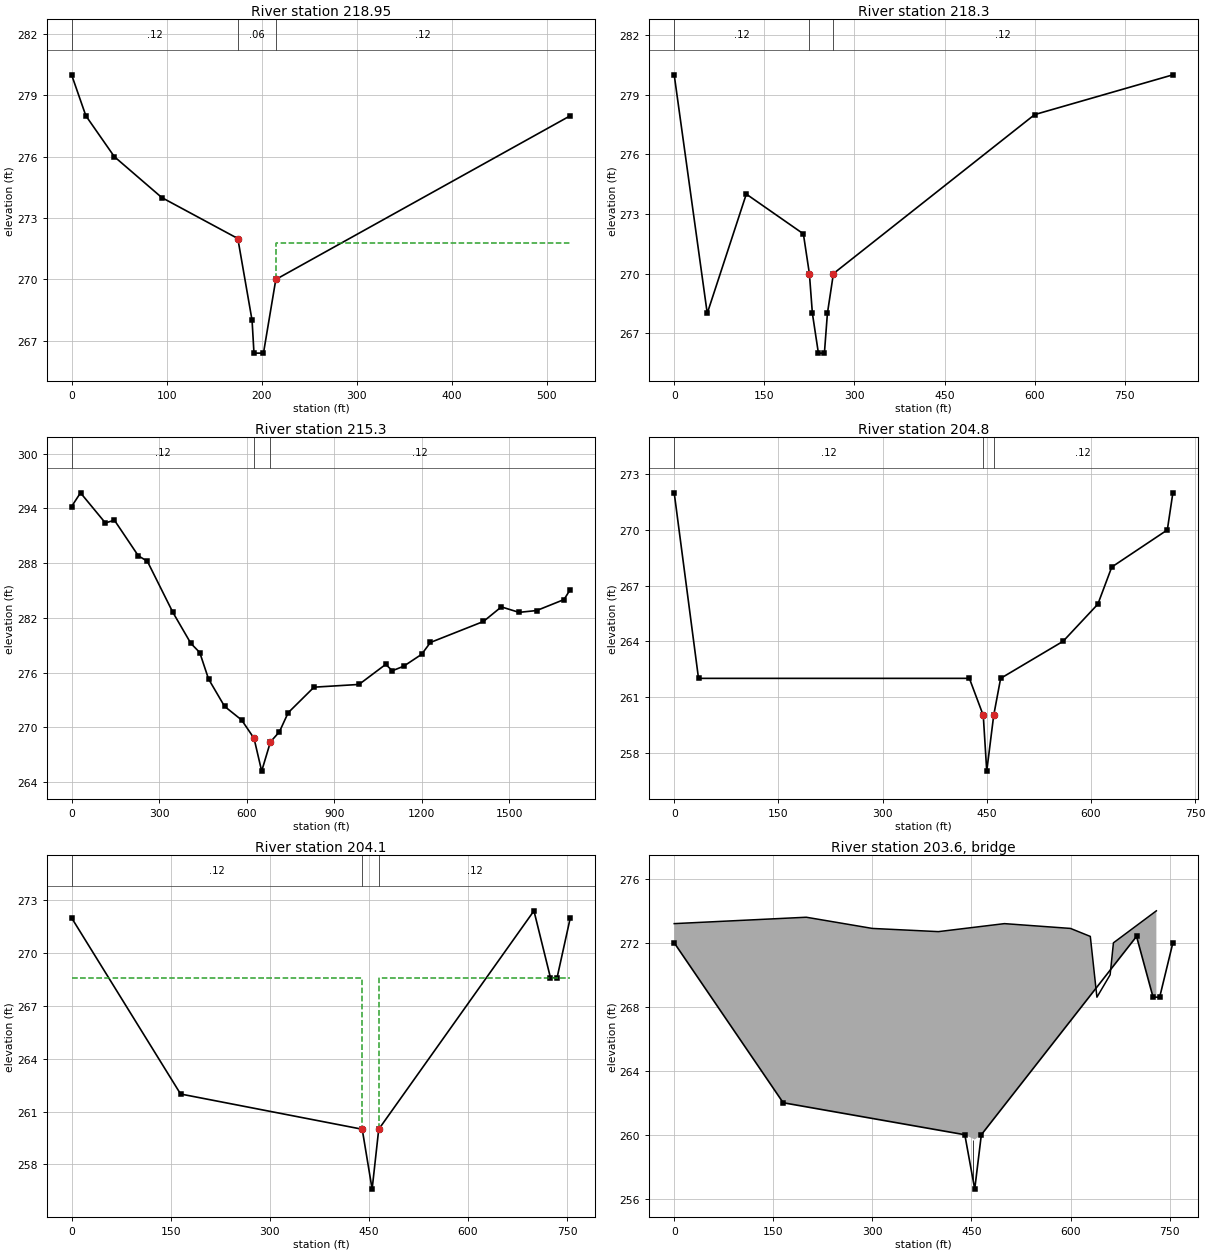
Type RM Length L Ch R = 1 ,218.95  ,65,65,65
#Sta/Elev= 10
       0     280      15     278      45     276      95     274     175     272
     190     268     192   266.4     202   266.4     215     270     525     278
#Mann= 3 , 0 , 0
       0     .12       0     175     .06       0     215     .12       0
#XS Ineff= 2 , 0
             175   271.8     215           271.8
Permanent Ineff=
       F       F
Bank Sta=175,215
XS Rating Curve= 0 ,0
Exp/Cntr=0.3,0.1

Type RM Length L Ch R = 1 ,218.3   ,300,300,300
#Sta/Elev= 12
       0     280      55     268     120     274     215     272     225     270
     230     268     240     266     250     266     255     268     265     270
     600     278     830     280
#Mann= 3 , 0 , 0
       0     .12       0     225     .06       0     265     .12       0
Bank Sta=225,265
XS Rating Curve= 0 ,0
Exp/Cntr=0.3,0.1

Type RM Length L Ch R = 1 ,215.3   ,1050,1050,1050
BEGIN DESCRIPTION:
RICH CNTY FEMA XS: U
END DESCRIPTION:
#Sta/Elev= 30
       0   294.2    30.5   295.7   115.7   292.4   146.7   292.7   228.6   288.8
   259.6   288.2     347   282.6   408.7   279.2   439.1   278.2   469.2   275.3
   524.1   272.3   582.7   270.8   625.1   268.8   651.3   265.2   681.3   268.4
   711.9   269.5   742.1   271.6   830.6   274.4   984.8   274.7  1076.4   276.9
    1099   276.2  1138.1   276.7  1199.4     278  1229.5   279.3  1411.2   281.6
  1472.6   283.2  1533.2   282.6  1593.7   282.8  1687.2     284  1708.8   285.1
#Mann= 3 , 0 , 0
       0     .12       0   625.1     .06       0   681.3     .12       0
Bank Sta=625.1,681.3
XS Rating Curve= 0 ,0
Exp/Cntr=0.3,0.1

Type RM Length L Ch R = 1 ,204.8   ,70,70,70
BEGIN DESCRIPTION:
RICH CNTY FEMA XS: T
END DESCRIPTION:
#Sta/Elev= 12
       0     272      35     262     425     262     445     260     450     257
     460     260     470     262     560     264     610     266     630     268
     710     270     718     272
#Mann= 3 , 0 , 0
       0     .12       0     445     .06       0     460     .12       0
Bank Sta=445,460
XS Rating Curve= 0 ,0
Exp/Cntr=0.3,0.1

Type RM Length L Ch R = 1 ,204.1   ,100,100,100
#Sta/Elev= 9
       0     272     165     262     440     260     455   256.6     465     260
     700   272.4     725   268.6     735   268.6     755     272
#Mann= 3 , 0 , 0
       0     .12       0     440     .06       0     465     .12       0
#XS Ineff= 2 , 0
             440   268.6     465           268.6
Permanent Ineff=
       F       F
Bank Sta=440,465
XS Rating Curve= 0 ,0
Exp/Cntr=0.3,0.1

Type RM Length L Ch R = 3 ,203.6   ,,,
BEGIN DESCRIPTION:
Bridge #13
END DESCRIPTION:
Bridge Culvert--1,0,-1,-1, 0
Deck Dist Width WeirC Skew NumUp NumDn MinLoCord MaxHiCord MaxSubmerge Is_Ogee
0.25,99.5,2.6,0, 15, 15, 268.6, , 0.98, 0, 0,0,,
       0     200     300     400     440     440     465     465     500     600
     630     640     660     665     730
   273.2   273.6   272.9   272.7   272.9   272.9 273.025 273.025   273.2   272.9
   272.4   268.6     270     272     274
   253.8   253.8   253.8   253.8   253.8   259.7   259.7   253.8   253.8   253.8
   253.8   253.8   253.8   253.8   253.8
       0     200     300     400     420     420     470     470     500     600
     630     640     660     665     730
   273.2   273.6   272.9   272.7   272.8   272.8  273.05  273.05   273.2   272.9
   272.4   268.6     270     272     274
   253.8   253.8   253.8   253.8   253.8   259.7   259.7   253.8   253.8   253.8
   253.8   253.8   253.8   253.8   253.8
Pier Skew, UpSta & Num, DnSta & Num=  ,452.5, 2 ,445, 2 , 0 , 0 , 0 ,,
     .01     .01
   256.6   259.7
     .01     .01
   253.8   259.7
BR Coef= 0 , 0 ,-1 ,0.9, 0 ,,,0.8006408,0,,2,259.7
WSPro=,,,, 1 ,,,, 0 ,,,, 0 ,,,,-1 ,-1 ,-1 , 0 , 0 , 0 , 0 , 0
BC Design=,, 0 ,, 0 ,,,,,,
BC Use User HTab Curves=0
BC User HTab FreeFlow(D)= 0