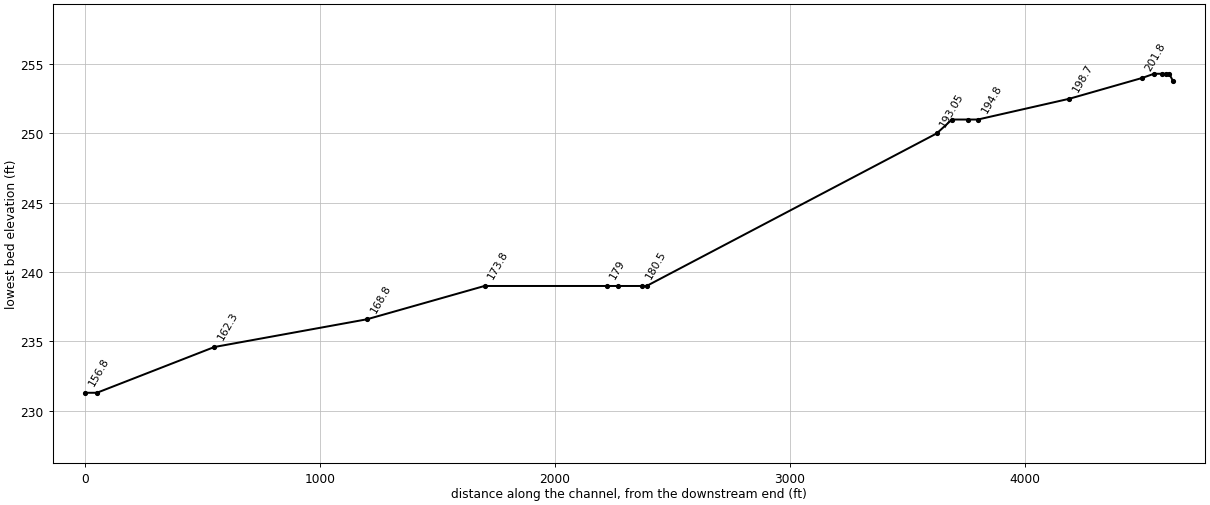
HEC-RAS study CCR_Stoop.prj: CCR_Stoop

--- CCR_Stoop.g01 (geometry) --- (continued)

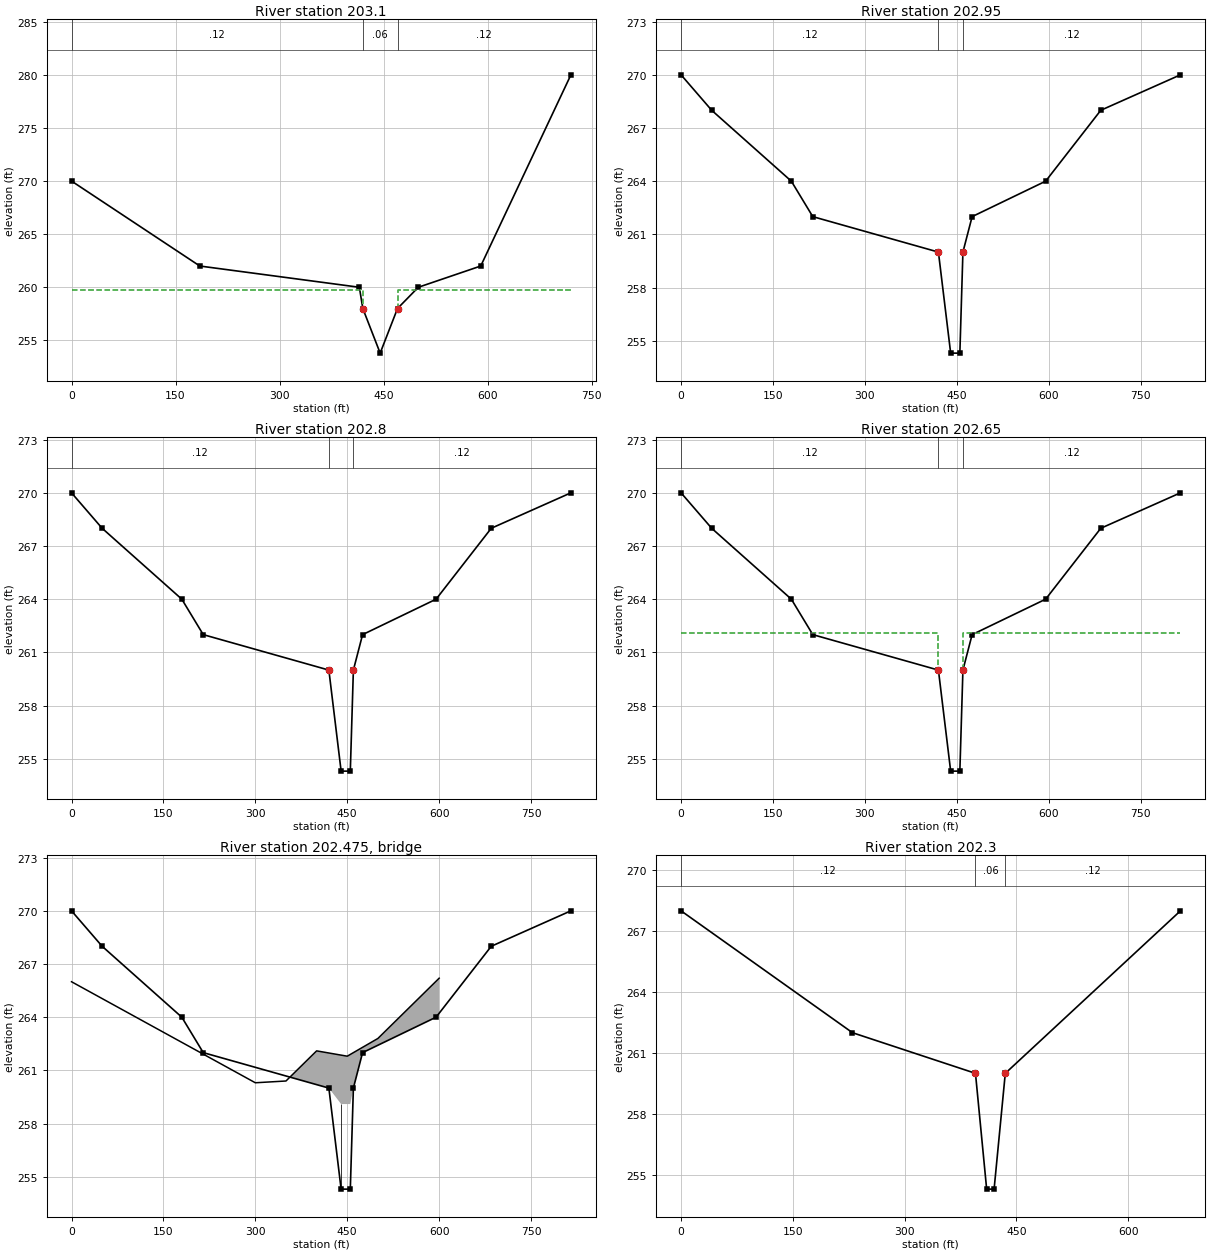
Type RM Length L Ch R = 1 ,203.1   ,15,15,15
#Sta/Elev= 9
       0     270     185     262     415     260     420     258     445   253.8
     470     258     500     260     590     262     720     280
#Mann= 3 , 0 , 0
       0     .12       0     420     .06       0     470     .12       0
#XS Ineff= 2 , 0
             420   259.7     470           259.7
Permanent Ineff=
       F       F
Bank Sta=420,470
XS Rating Curve= 0 ,0
Exp/Cntr=0.3,0.1

Type RM Length L Ch R = 1 ,202.95  ,15,15,15
#Sta/Elev= 12
       0     270      50     268     180     264     215     262     420     260
     440   254.3     455   254.3     460     260     475     262     595     264
     685     268     815     270
#Mann= 3 , 0 , 0
       0     .12       0     420     .06       0     460     .12       0
Bank Sta=420,460
XS Rating Curve= 0 ,0
Exp/Cntr=0.3,0.1

Type RM Length L Ch R = 1 ,202.8   ,15,15,15
#Sta/Elev= 12
       0     270      50     268     180     264     215     262     420     260
     440   254.3     455   254.3     460     260     475     262     595     264
     685     268     815     270
#Mann= 3 , 0 , 0
       0     .12       0     420     .06       0     460     .12       0
Bank Sta=420,460
XS Rating Curve= 0 ,0
Exp/Cntr=0.3,0.1

Type RM Length L Ch R = 1 ,202.65  ,35,35,35
#Sta/Elev= 12
       0     270      50     268     180     264     215     262     420     260
     440   254.3     455   254.3     460     260     475     262     595     264
     685     268     815     270
#Mann= 3 , 0 , 0
       0     .12       0     420     .06       0     460     .12       0
#XS Ineff= 2 , 0
             420   262.1     460           262.1
Permanent Ineff=
       F       F
Bank Sta=420,460
XS Rating Curve= 0 ,0
Exp/Cntr=0.3,0.1

Type RM Length L Ch R = 3 ,202.475 ,,,
BEGIN DESCRIPTION:
Bridge #12
END DESCRIPTION:
Bridge Culvert--1,0,-1,-1, 0
Deck Dist Width WeirC Skew NumUp NumDn MinLoCord MaxHiCord MaxSubmerge Is_Ogee
0.25,34.5,2.6,0, 11, 11, 262.1, , 0.98, 0, 0,0,,
       0     300     350     400     420     420     450     460     460     500
     600
     266   260.3   260.4   262.1  261.98  261.98   261.8     262     262   262.8
   266.2
   254.3   254.3   254.3   254.3   254.3   259.1   259.1   259.1   254.3   254.3
   254.3
       0     300     350     395     395     400     435     435     450     500
     600
     266   260.3   260.4  261.93  261.93   262.1  261.89  261.89   261.8   262.8
   266.2
   254.3   254.3   254.3   254.3   259.1   259.1   259.1   254.3   254.3   254.3
   254.3
Pier Skew, UpSta & Num, DnSta & Num=  ,440, 2 ,415, 2 , 0 , 0 , 0 ,,
     .15     .15
   254.3   259.1
     .15     .15
   254.3   259.1
BR Coef= 0 , 0 ,-1 ,1.25, 0 ,,,0.8006408,0,,2,259.1
WSPro=,,,, 1 ,,,, 0 ,,,, 0 ,,,,-1 ,-1 ,-1 , 0 , 0 , 0 , 0 , 0
BC Design=,, 0 ,, 0 ,,,,,,
BC Use User HTab Curves=0
BC User HTab FreeFlow(D)= 0

Type RM Length L Ch R = 1 ,202.3   ,50,50,50
#Sta/Elev= 7
       0     268     230     262     395     260     410   254.3     420   254.3
     435     260     670     268
#Mann= 3 , 0 , 0
       0     .12       0     395     .06       0     435     .12       0
#XS Ineff= 2 , 0
             395   259.1     435           259.1
Permanent Ineff=
       F       F
Bank Sta=395,435
XS Rating Curve= 0 ,0
Exp/Cntr=0.3,0.1

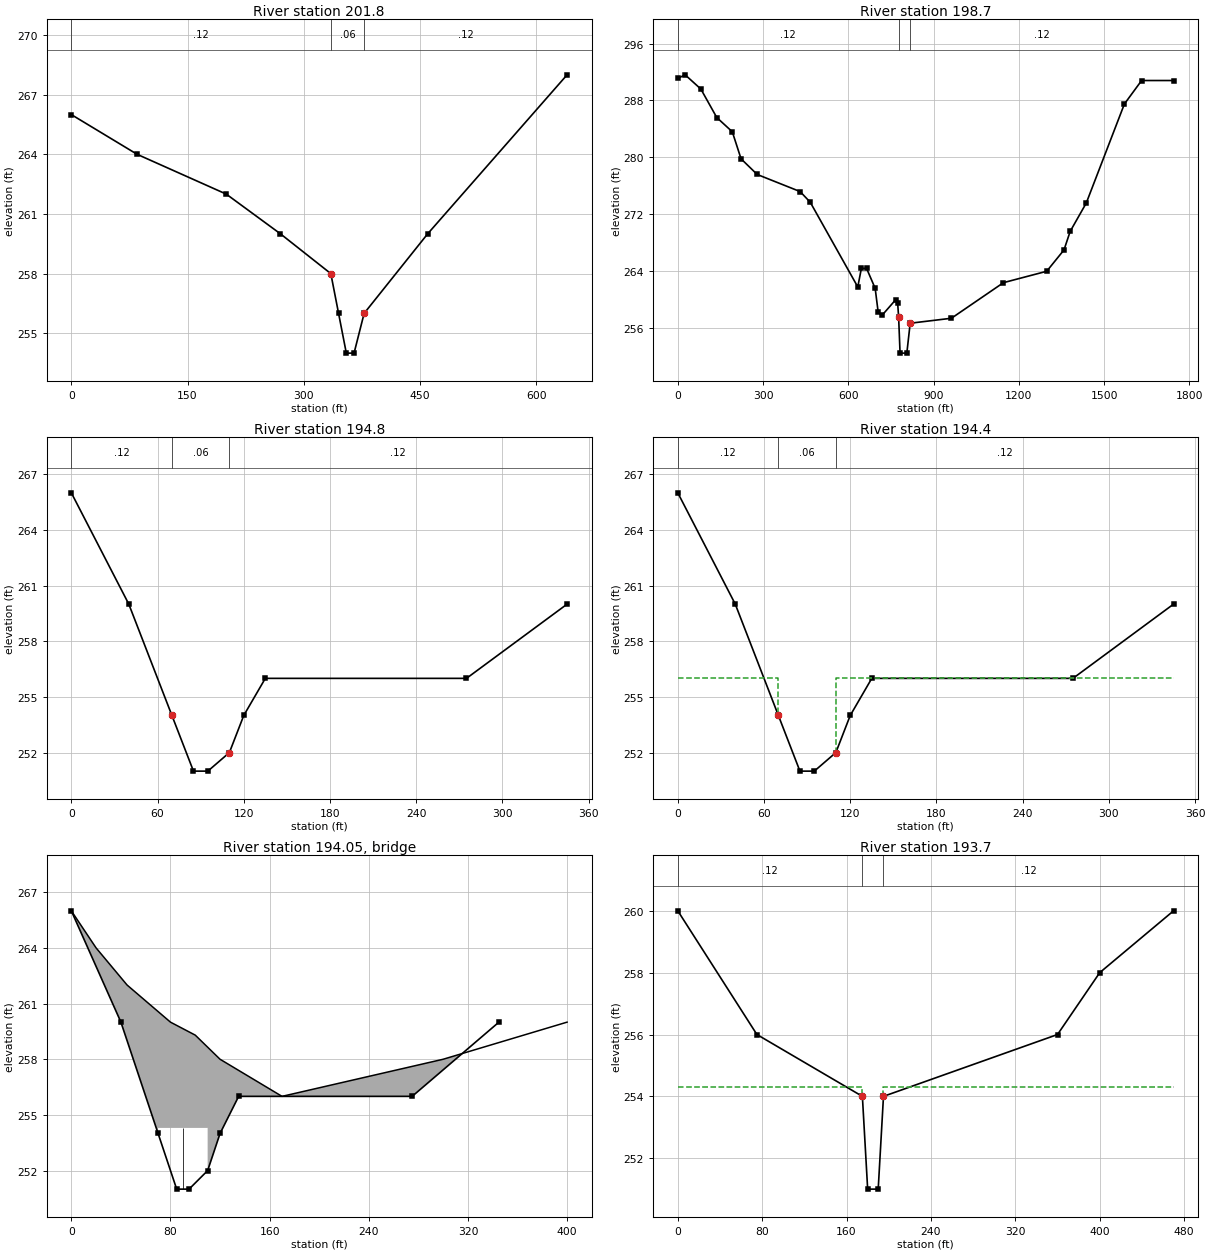
Type RM Length L Ch R = 1 ,201.8   ,310,310,310
BEGIN DESCRIPTION:
RICH CNTY FEMA XS: S
END DESCRIPTION:
#Sta/Elev= 11
       0     266      85     264     200     262     270     260     335     258
     345     256     355     254     365     254     378     256     460     260
     640     268
#Mann= 3 , 0 , 0
       0     .12       0     335     .06       0     378     .12       0
Bank Sta=335,378
XS Rating Curve= 0 ,0
Exp/Cntr=0.3,0.1

Type RM Length L Ch R = 1 ,198.7   ,390,390,390
#Sta/Elev= 30
       0   291.1    25.9   291.6    81.2   289.6   137.2   285.6   191.8   283.6
   222.6   279.8   279.4   277.6   430.4   275.2   466.1   273.7   633.4   261.8
     646   264.4   664.4   264.4   694.6   261.6     705   258.3   718.5   257.8
   766.7     260   773.6   259.6   777.1   257.6   782.2   252.5     806   252.5
   817.8   256.7   962.9   257.4    1146   262.4  1298.2     264  1359.1     267
  1380.8   269.6  1437.6   273.6  1571.6   287.5  1632.2   290.8  1744.6   290.8
#Mann= 3 , 0 , 0
       0     .12       0   777.1     .06       0   817.8     .12       0
Bank Sta=777.1,817.8
XS Rating Curve= 0 ,0
Exp/Cntr=0.3,0.1

Type RM Length L Ch R = 1 ,194.8   ,40,40,40
#Sta/Elev= 10
       0     266      40     260      70     254      85     251      95     251
     110     252     120     254     135     256     275     256     345     260
#Mann= 3 , 0 , 0
       0     .12       0      70     .06       0     110     .12       0
Bank Sta=70,110
XS Rating Curve= 0 ,0
Exp/Cntr=0.3,0.1

Type RM Length L Ch R = 1 ,194.4   ,70,70,60
BEGIN DESCRIPTION:
RICH CNTY FEMA XS: R
END DESCRIPTION:
#Sta/Elev= 10
       0     266      40     260      70     254      85     251      95     251
     110     252     120     254     135     256     275     256     345     260
#Mann= 3 , 0 , 0
       0     .12       0      70     .06       0     110     .12       0
#XS Ineff= 2 , 0
              70     256     110             256
Permanent Ineff=
       F       F
Bank Sta=70,110
XS Rating Curve= 0 ,0
Exp/Cntr=0.3,0.1

Type RM Length L Ch R = 3 ,194.05  ,,,
BEGIN DESCRIPTION:
Bridge #11
END DESCRIPTION:
Bridge Culvert--1,0,-1,-1, 0
Deck Dist Width WeirC Skew NumUp NumDn MinLoCord MaxHiCord MaxSubmerge Is_Ogee
0.25,69.5,2.6,0, 13, 13, 256, , 0.98, 0, 0,0,,
       0      20      45      70      70      80     100     110     110     120
     170     300     400
     266     264     262260.5714260.5714     260   259.3  258.65  258.65     258
     256     258     260
     251     251     251     251   254.3   254.3   254.3   254.3     251     251
     251     251     251
       0      20      45      80     100     120     170     175     175     195
     195     300     400
     266     264     262     260   259.3     258     256256.0769256.0769256.3846
256.3846     258     260
     251     251     251     251     251     251     251     251   254.3   254.3
     251     251     251
Pier Skew, UpSta & Num, DnSta & Num=  ,90, 2 ,185, 2 , 0 , 0 , 0 ,,
      .3      .3
     251   254.3
      .3      .3
     251   254.3
BR Coef= 0 , 0 ,-1 ,1.25, 0 ,,,0.8006408,0,,2,254.3
WSPro=,,,, 1 ,,,, 0 ,,,, 0 ,,,,-1 ,-1 ,-1 , 0 , 0 , 0 , 0 , 0
BC Design=,, 0 ,, 0 ,,,,,,
BC Use User HTab Curves=0
BC User HTab FreeFlow(D)= 0

Type RM Length L Ch R = 1 ,193.7   ,65,65,65
#Sta/Elev= 9
       0     260      75     256     175     254     180     251     190     251
     195     254     360     256     400     258     470     260
#Mann= 3 , 0 , 0
       0     .12       0     175     .06       0     195     .12       0
#XS Ineff= 2 , 0
             175   254.3     195           254.3
Permanent Ineff=
       F       F
Bank Sta=175,195
XS Rating Curve= 0 ,0
Exp/Cntr=0.3,0.1

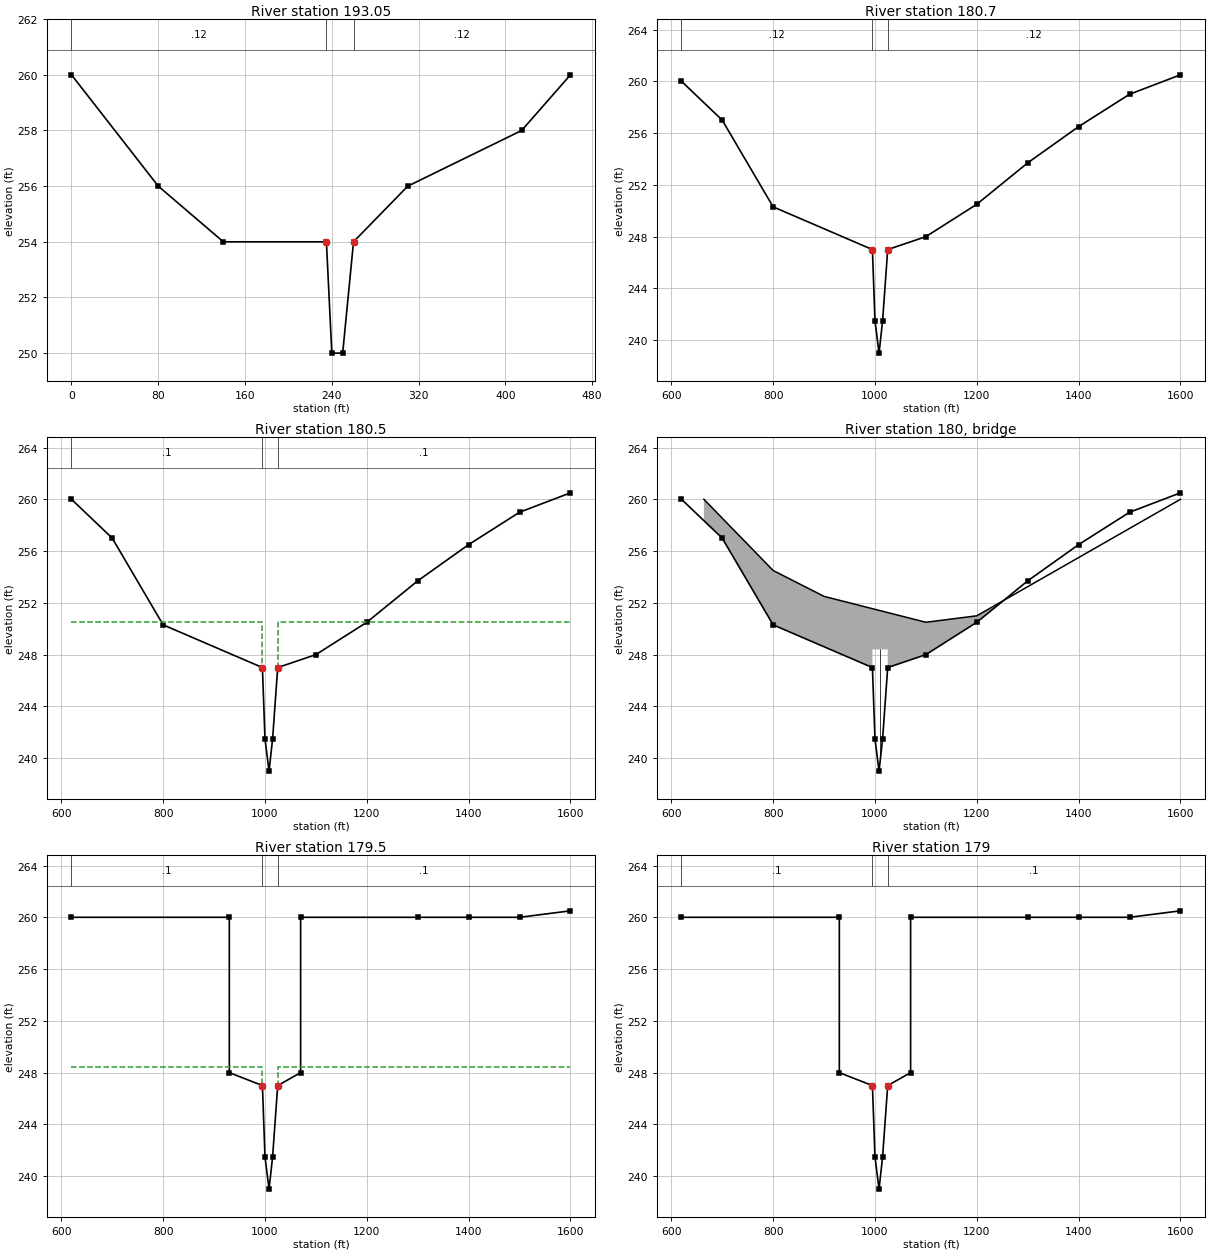
Type RM Length L Ch R = 1 ,193.05  ,1235,1235,1235
BEGIN DESCRIPTION:
RICH CNTY FEMA XS: Q
END DESCRIPTION:
#Sta/Elev= 10
       0     260      80     256     140     254     235     254     240     250
     250     250     260     254     310     256     415     258     460     260
#Mann= 3 , 0 , 0
       0     .12       0     235     .06       0     260     .12       0
Bank Sta=235,260
XS Rating Curve= 0 ,0
Exp/Cntr=0.3,0.1

Type RM Length L Ch R = 1 ,180.7   ,20,20,20
BEGIN DESCRIPTION:
RICH CNTY FEMA XS: P
END DESCRIPTION:
#Sta/Elev= 14
     620     260     700     257     800   250.3     995     247    1000   241.5
    1008     239    1015   241.5    1025     247    1100     248    1200   250.5
    1300   253.7    1400   256.5    1500     259    1600   260.5
#Mann= 3 , 0 , 0
     620     .12       0     995     .06       0    1025     .12       0
Bank Sta=995,1025
XS Rating Curve= 0 ,0
Exp/Cntr=0.3,0.1

Type RM Length L Ch R = 1 ,180.5   ,100,100,100
#Sta/Elev= 14
     620     260     700     257     800   250.3     995     247    1000   241.5
    1008     239    1015   241.5    1025     247    1100     248    1200   250.5
    1300   253.7    1400   256.5    1500     259    1600   260.5
#Mann= 3 , 0 , 0
     620      .1       0     995     .06       0    1025      .1       0
#XS Ineff= 2 , 0
             995   250.5    1025           250.5
Permanent Ineff=
       F       F
Bank Sta=995,1025
XS Rating Curve= 0 ,0
Exp/Cntr=0.3,0.1

Type RM Length L Ch R = 3 ,180     ,,,
BEGIN DESCRIPTION:
Bridge #10
END DESCRIPTION:
Bridge Culvert--1,0,-1,-1, 0
Deck Dist Width WeirC Skew NumUp NumDn MinLoCord MaxHiCord MaxSubmerge Is_Ogee
0.25,99.5,2.6,0, 11, 11, 250.5, , 0.98, 0, 0,0,,
     664     800     900     995     995    1000    1025    1025    1100    1200
    1600
     260   254.5   252.5  251.55  251.55   251.5  251.25  251.25   250.5     251
     260
     239     239     239     239   248.4   248.4   248.4     239     239     239
     239
     664     800     900     995     995    1000    1025    1025    1100    1200
    1600
     260   254.5   252.5  251.55  251.55   251.5  251.25  251.25   250.5     251
     260
     239     239     239     239   248.4   248.4   248.4     239     239     239
     239
Pier Skew, UpSta & Num, DnSta & Num=  ,1010, 2 ,1010, 2 , 0 , 0 , 0 ,,
      .3      .3
     239   248.4
      .3      .3
     239   248.4
BR Coef= 0 , 0 ,-1 ,0.9, 0 ,,,0.8006408,0,,2,248.4
WSPro=,,,, 1 ,,,, 0 ,,,, 0 ,,,,-1 ,-1 ,-1 , 0 , 0 , 0 , 0 , 0
BC Design=,, 0 ,, 0 ,,,,,,
BC Use User HTab Curves=0
BC User HTab FreeFlow(D)= 0

Type RM Length L Ch R = 1 ,179.5   ,50,50,50
#Sta/Elev= 14
     620     260     930     260     930     248     995     247    1000   241.5
    1008     239    1015   241.5    1025     247    1070     248    1070     260
    1300     260    1400     260    1500     260    1600   260.5
#Mann= 3 , 0 , 0
     620      .1       0     995     .06       0    1025      .1       0
#XS Ineff= 2 , 0
             995   248.4    1025           248.4
Permanent Ineff=
       F       F
Bank Sta=995,1025
XS Rating Curve= 0 ,0
Exp/Cntr=0.3,0.1

Type RM Length L Ch R = 1 ,179     ,520,520,520
BEGIN DESCRIPTION:
RICH CNTY FEMA XS: O
END DESCRIPTION:
#Sta/Elev= 14
     620     260     930     260     930     248     995     247    1000   241.5
    1008     239    1015   241.5    1025     247    1070     248    1070     260
    1300     260    1400     260    1500     260    1600   260.5
#Mann= 3 , 0 , 0
     620      .1       0     995     .06       0    1025      .1       0
Bank Sta=995,1025
XS Rating Curve= 0 ,0
Exp/Cntr=0.3,0.1

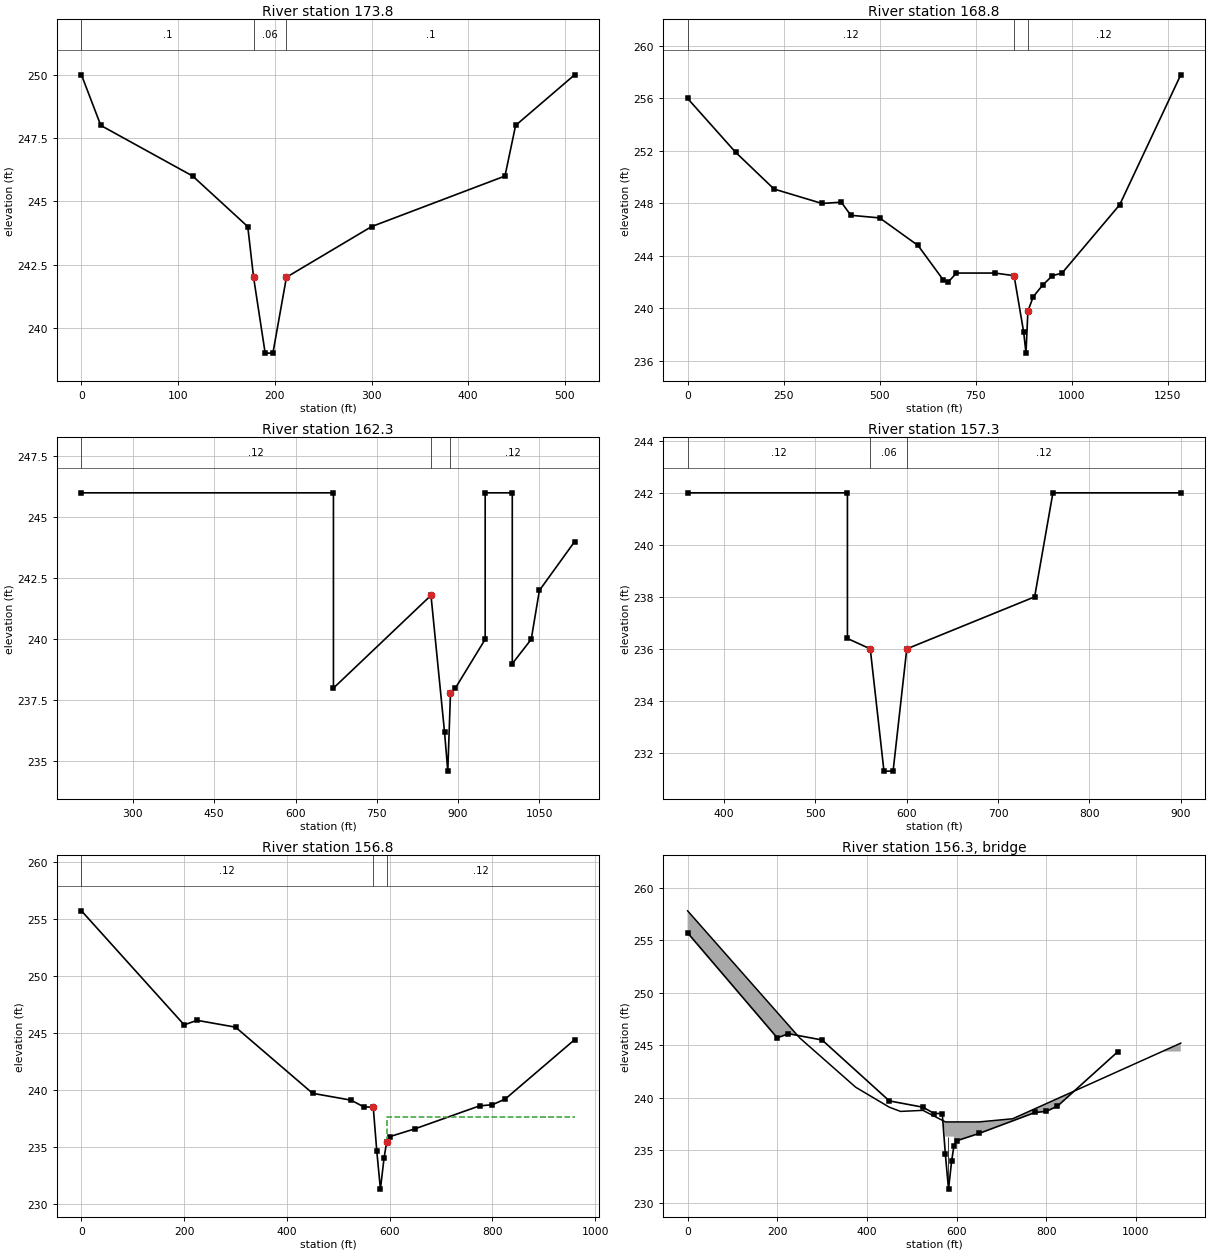
Type RM Length L Ch R = 1 ,173.8   ,500,500,500
BEGIN DESCRIPTION:
RICH CNTY FEMA XS: N
END DESCRIPTION:
#Sta/Elev= 12
       0     250      20     248     115     246     172     244     178     242
     190     239     198     239     212     242     300     244     438     246
     449     248     510     250
#Mann= 3 , 0 , 0
       0      .1       0     178     .06       0     212      .1       0
Bank Sta=178,212
XS Rating Curve= 0 ,0
Exp/Cntr=0.3,0.1

Type RM Length L Ch R = 1 ,168.8   ,650,650,650
BEGIN DESCRIPTION:
RICH CNTY FEMA XS: M
END DESCRIPTION:
#Sta/Elev= 22
       0     256     125   251.9     225   249.1     350     248     400   248.1
     425   247.1     500   246.9     600   244.8     665   242.2     678     242
     700   242.7     800   242.7     850   242.5     875   238.2     881   236.6
     886   239.8     900   240.9     925   241.8     950   242.5     975   242.7
    1125   247.9    1284   257.8
#Mann= 3 , 0 , 0
       0     .12       0     850     .06       0     886     .12       0
Bank Sta=850,886
XS Rating Curve= 0 ,0
Exp/Cntr=0.3,0.1

Type RM Length L Ch R = 1 ,162.3   ,500,500,500
#Sta/Elev= 15
     205     246     670     246     670     238     850   241.8     875   236.2
     881   234.6     886   237.8     895     238     950     240     950     246
    1000     246    1000     239    1035     240    1050     242    1115     244
#Mann= 3 , 0 , 0
     205     .12       0     850     .06       0     886     .12       0
Bank Sta=850,886
XS Rating Curve= 0 ,0
Exp/Cntr=0.3,0.1

Type RM Length L Ch R = 1 ,157.3   ,50,50,50
BEGIN DESCRIPTION:
RICH CNTY FEMA XS: L
END DESCRIPTION:
#Sta/Elev= 10
     360     242     535     242     535   236.4     560     236     575   231.3
     585   231.3     600     236     740     238     760     242     900     242
#Mann= 3 , 0 , 0
     360     .12       0     560     .06       0     600     .12       0
Bank Sta=560,600
XS Rating Curve= 0 ,0
Exp/Cntr=0.3,0.1

Type RM Length L Ch R = 1 ,156.8   ,100,100,100
#Sta/Elev= 18
       0   255.7     200   245.7     225   246.1     300   245.5     450   239.7
     525   239.1     550   238.5     568   238.5     575   234.6     582   231.3
     589     234     594   235.4     600   235.9     650   236.6     775   238.6
     800   238.7     825   239.2     960   244.4
#Mann= 3 , 0 , 0
       0     .12       0     568     .06       0     594     .12       0
#XS Ineff= 2 , 0
             568   237.6     594           237.6
Permanent Ineff=
       F       F
Bank Sta=568,594
XS Rating Curve= 0 ,0
Exp/Cntr=0.5,0.3

Type RM Length L Ch R = 3 ,156.3   ,,,
BEGIN DESCRIPTION:
Bridge #9
END DESCRIPTION:
Bridge Culvert--1,0,-1,-1, 0
Deck Dist Width WeirC Skew NumUp NumDn MinLoCord MaxHiCord MaxSubmerge Is_Ogee
0.25,99.5,2.8,0, 14, 13, 237.6, , 0.98, 0, 0,0,,
       0     250     375     450     475     525     568     568     575     594
     594     650     725    1100
   257.8   245.7     241   239.1   238.7   238.8 237.854 237.854   237.7   237.7
   237.7   237.7     238   245.2
   231.3   231.3   231.3   231.3   231.3   231.3   231.3   236.3   236.3   236.3
   231.3   231.3   231.3   231.3
       0     250     375     375     411     411     450     475     525     575
     650     725    1100
   257.8   245.7     241     241 240.088 240.088   239.1   238.7   238.8   237.7
   237.7     238   245.2
   231.3   231.3   231.3   236.3   236.3   231.3   231.3   231.3   231.3   231.3
   231.3   231.3   231.3
Pier Skew, UpSta & Num, DnSta & Num=  ,581, 2 ,393, 2 , 0 , 0 , 0 ,,
       1       1
   231.3   236.3
       1       1
     232   236.3
BR Coef= 0 , 0 ,-1 ,1.25, 0 ,,,0.7955573,0,,2,236.3
WSPro=,,,, 1 ,,,, 0 ,,,, 0 ,,,,-1 ,-1 ,-1 , 0 , 0 , 0 , 0 , 0
BC Design=,, 0 ,, 0 ,,,,,,
BC Use User HTab Curves=0
BC User HTab FreeFlow(D)= 0