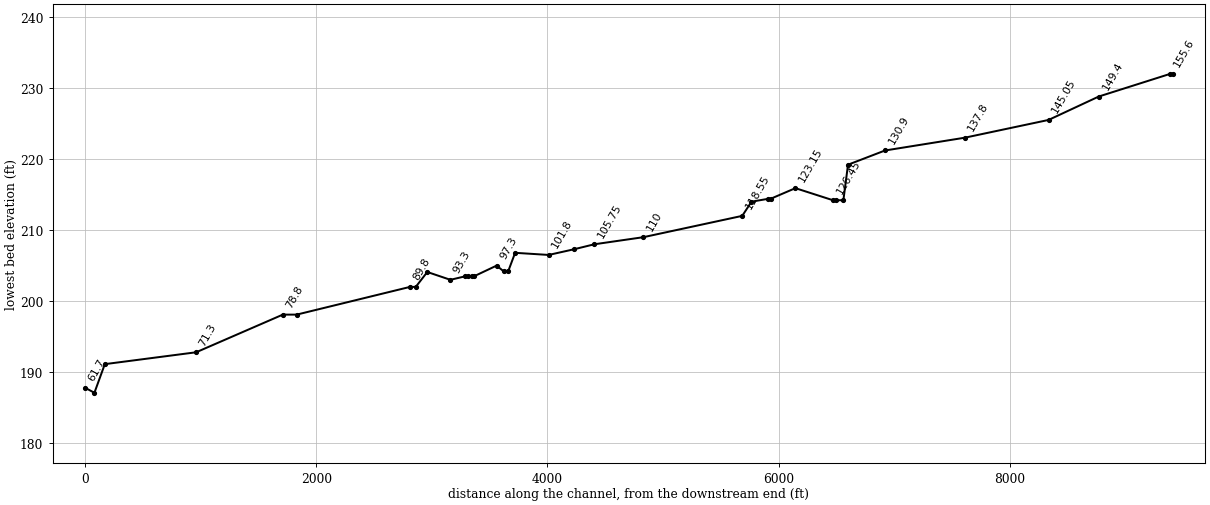
HEC-RAS study CCR_Stoop.prj: CCR_Stoop

--- CCR_Stoop.g01 (geometry) --- (continued)

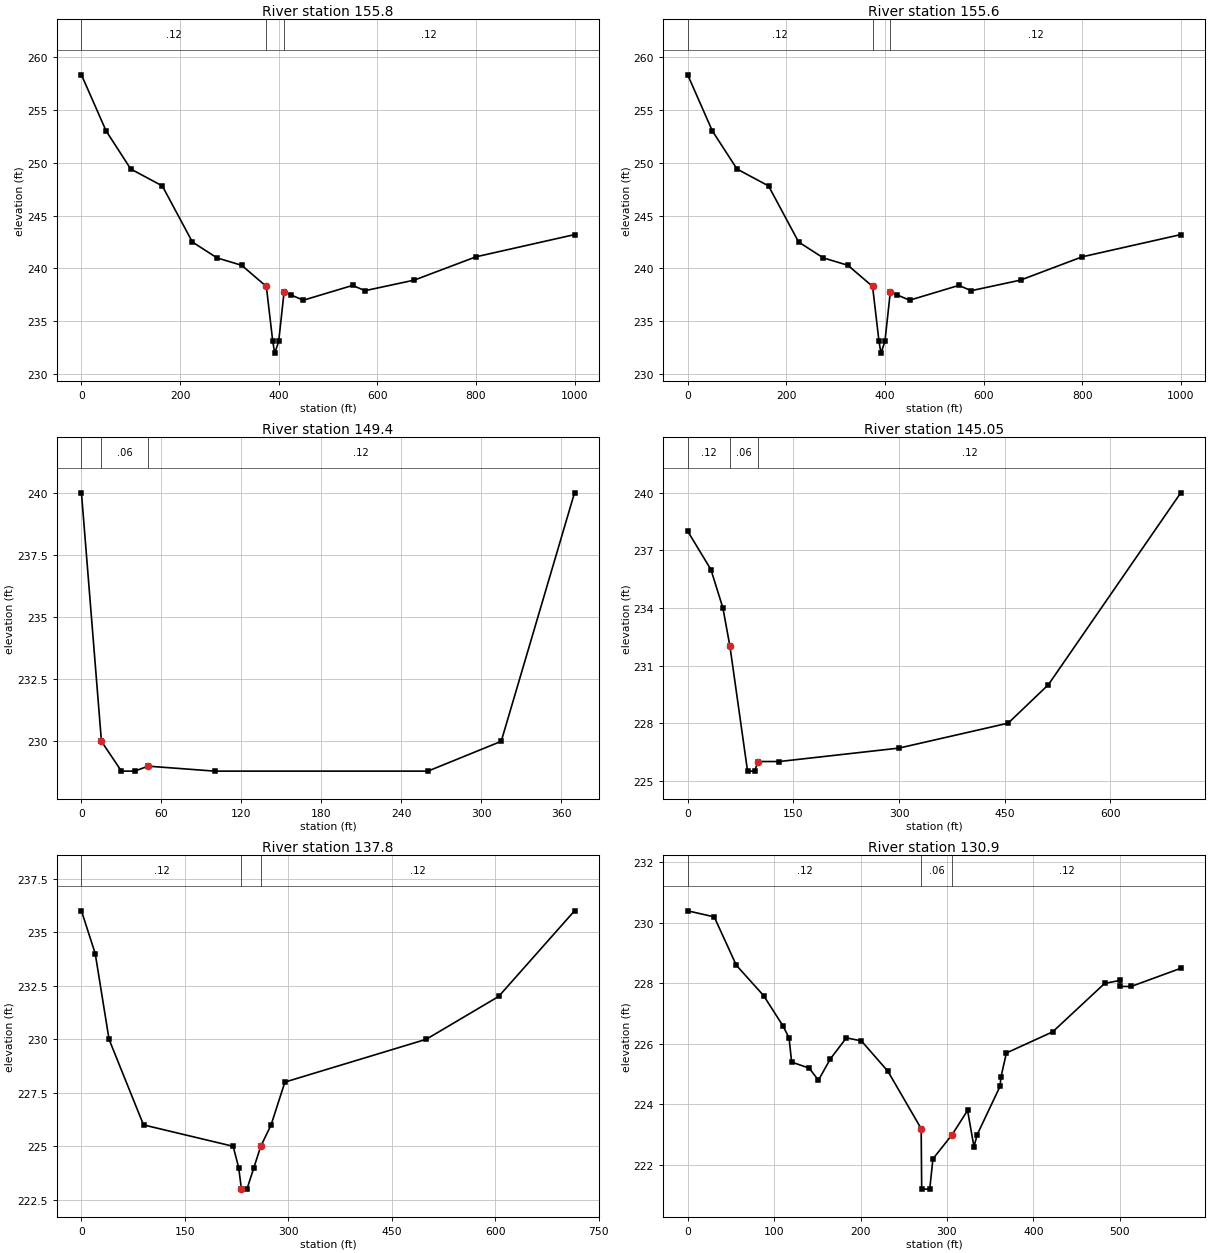
Type RM Length L Ch R = 1 ,155.8   ,20,20,20
#Sta/Elev= 19
       0   258.3      50     253     100   249.4     164   247.8     225   242.5
     275     241     325   240.3     375   238.3     388   233.1     392     232
     400   233.1     411   237.8     425   237.5     450     237     550   238.4
     575   237.9     675   238.9     800   241.1    1000   243.2
#Mann= 3 , 0 , 0
       0     .12       0     375     .06       0     411     .12       0
#XS Ineff= 2 , 0
             375   236.3     411           236.3
Permanent Ineff=
       F       F
Bank Sta=375,411
XS Rating Curve= 0 ,0
Exp/Cntr=0.5,0.3

Type RM Length L Ch R = 1 ,155.6   ,620,620,620
BEGIN DESCRIPTION:
RICH CNTY FEMA XS: K
END DESCRIPTION:
#Sta/Elev= 19
       0   258.3      50     253     100   249.4     164   247.8     225   242.5
     275     241     325   240.3     375   238.3     388   233.1     392     232
     400   233.1     411   237.8     425   237.5     450     237     550   238.4
     575   237.9     675   238.9     800   241.1    1000   243.2
#Mann= 3 , 0 , 0
       0     .12       0     375     .06       0     411     .12       0
Bank Sta=375,411
XS Rating Curve= 0 ,0
Exp/Cntr=0.3,0.1

Type RM Length L Ch R = 1 ,149.4   ,435,435,435
BEGIN DESCRIPTION:
RICH CNTY FEMA XS: J
END DESCRIPTION:
#Sta/Elev= 9
       0     240      15     230      30   228.8      40   228.8      50     229
     100   228.8     260   228.8     315     230     370     240
#Mann= 3 , 0 , 0
       0     .12       0      15     .06       0      50     .12       0
Bank Sta=15,50
XS Rating Curve= 0 ,0
Exp/Cntr=0.3,0.1

Type RM Length L Ch R = 1 ,145.05  ,725,725,725
BEGIN DESCRIPTION:
RICH CNTY FEMA XS: I
END DESCRIPTION:
#Sta/Elev= 12
       0     238      33     236      50     234      60     232      85   225.5
      95   225.5     100     226     130     226     300   226.7     455     228
     512     230     700     240
#Mann= 3 , 0 , 0
       0     .12       0      60     .06       0     100     .12       0
Bank Sta=60,100
XS Rating Curve= 0 ,0
Exp/Cntr=0.3,0.1

Type RM Length L Ch R = 1 ,137.8   ,690,690,690
#Sta/Elev= 15
       0     236      20     234      40     230      90     226     220     225
     228     224     232     223     240     223     250     224     260     225
     275     226     295     228     500     230     605     232     715     236
#Mann= 3 , 0 , 0
       0     .12       0     232     .06       0     260     .12       0
Bank Sta=232,260
XS Rating Curve= 0 ,0
Exp/Cntr=0.3,0.1

Type RM Length L Ch R = 1 ,130.9   ,320,320,320
BEGIN DESCRIPTION:
RICH CNTY FEMA XS: H
END DESCRIPTION:
#Sta/Elev= 30
       0   230.4    30.7   230.2    56.3   228.6    87.8   227.6   110.2   226.6
   117.3   226.2   120.3   225.4   140.6   225.2   151.3   224.8     165   225.5
   183.6   226.2     201   226.1   231.6   225.1   270.2   223.2   270.8   221.2
   280.1   221.2   283.8   222.2     306     223   323.9   223.8   331.3   222.6
     335     223   361.5   224.6   362.5   224.9   368.8   225.7   422.4   226.4
   482.5     228   500.1   228.1   500.7   227.9   513.2   227.9   570.6   228.5
#Mann= 3 , 0 , 0
       0     .12       0   270.2     .06       0     306     .12       0
Bank Sta=270.2,306
XS Rating Curve= 0 ,0
Exp/Cntr=0.3,0.1

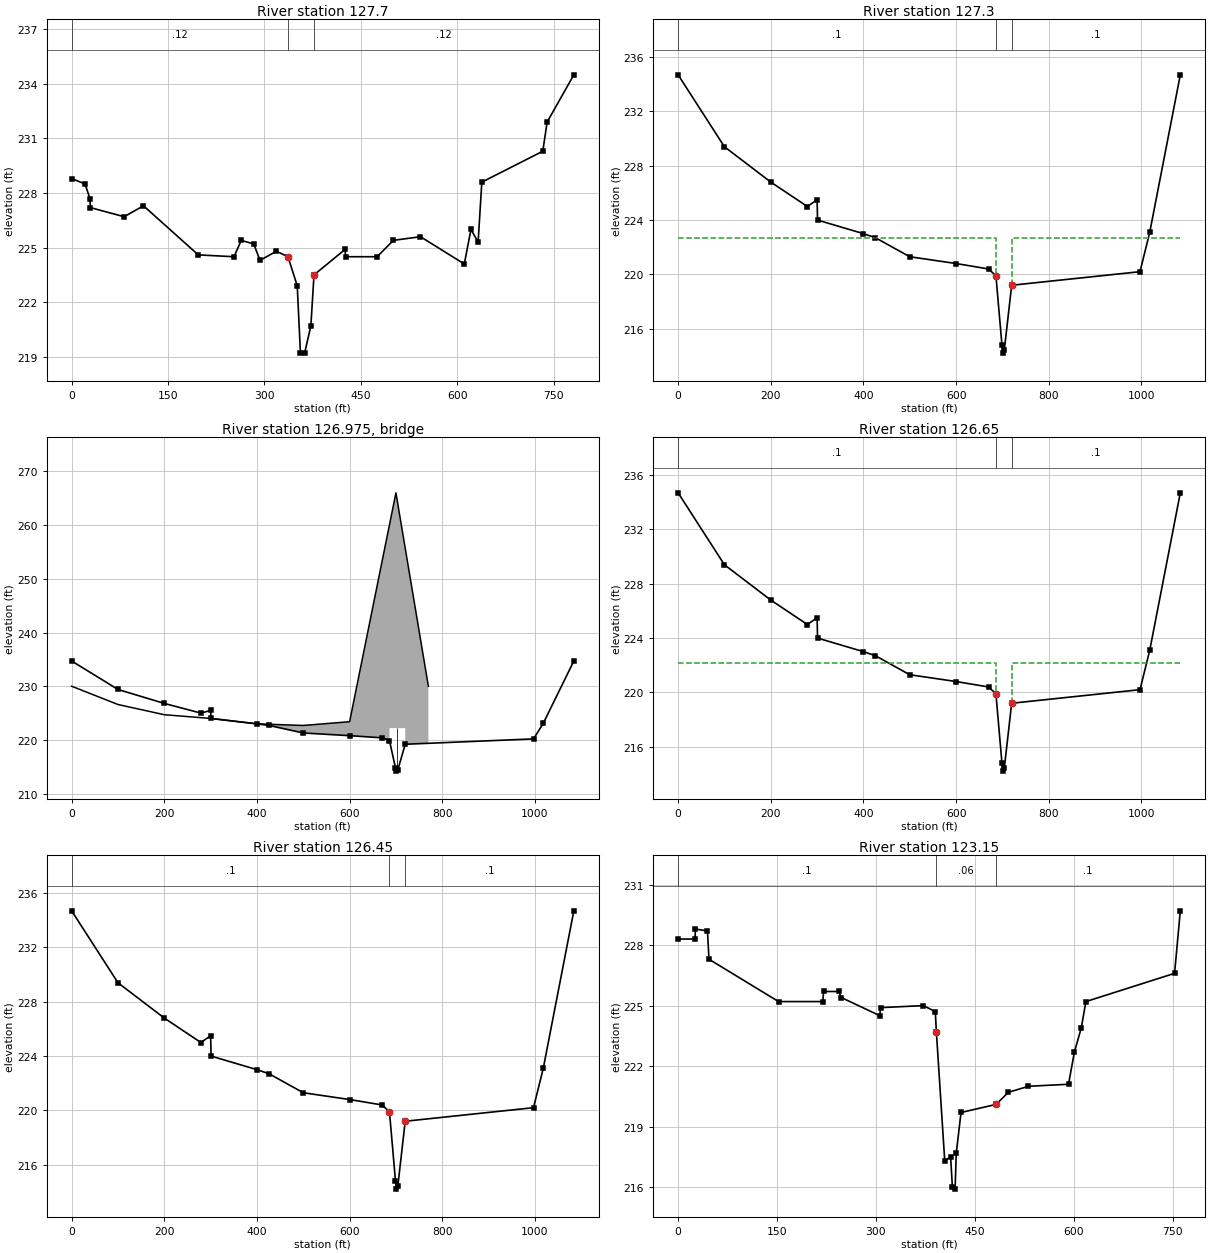
Type RM Length L Ch R = 1 ,127.7   ,40,40,40
#Sta/Elev= 30
       0   228.8    20.8   228.5    28.5   227.7    29.1   227.2    81.7   226.7
   111.8   227.3   197.1   224.6   252.7   224.5     264   225.4   283.5   225.2
   293.1   224.3   318.7   224.8   336.7   224.5   351.1   222.9   356.1   219.2
   362.6   219.2   372.3   220.7   377.2   223.5   425.5   224.9   426.3   224.5
   475.4   224.5   500.8   225.4   542.9   225.6   611.1   224.1   621.5     226
   632.6   225.3   638.4   228.6   733.3   230.3     740   231.9   781.6   234.5
#Mann= 3 , 0 , 0
       0     .12       0   336.7     .06       0   377.2     .12       0
Bank Sta=336.7,377.2
XS Rating Curve= 0 ,0
Exp/Cntr=0.3,0.1

Type RM Length L Ch R = 1 ,127.3   ,65,65,65
#Sta/Elev= 19
       0   234.7     100   229.4     200   226.8     279     225     300   225.5
     301     224     400     223     426   222.7     500   221.3     600   220.8
     670   220.4     686   219.9     699   214.8     701   214.2     704   214.4
     720   219.2     997   220.2    1018   223.1    1084   234.7
#Mann= 3 , 0 , 0
       0      .1       0     686     .06       0     720      .1       0
#XS Ineff= 2 , 0
             686   222.7     720           222.7
Permanent Ineff=
       F       F
Bank Sta=686,720
XS Rating Curve= 0 ,0
Exp/Cntr=0.3,0.1

Type RM Length L Ch R = 3 ,126.975 ,,,
BEGIN DESCRIPTION:
Bridge #8
END DESCRIPTION:
Bridge Culvert--1,0,-1,-1, 0
Deck Dist Width WeirC Skew NumUp NumDn MinLoCord MaxHiCord MaxSubmerge Is_Ogee
0.25,64.5,2.8,0, 13, 13, 222.7, , 0.98, 0, 0,0,,
       0     100     200     301     400     500     600     686     686     700
     720     720     770
     230   226.6   224.7     224     223   222.7   223.4 260.036 260.036     266
255.7143255.7143     230
   214.2   214.2   214.2   214.2   214.2   214.2   214.2   214.2   222.2   222.2
   222.2   214.2   214.2
       0     100     200     301     400     500     600     686     686     700
     720     720     770
     230   226.6   224.7     224     223   222.7   223.4 260.036 260.036     266
255.7143255.7143     230
   214.2   214.2   214.2   214.2   214.2   214.2   214.2   214.2   222.2   222.2
   222.2   214.2   214.2
Pier Skew, UpSta & Num, DnSta & Num=  ,703, 2 ,703, 2 , 0 , 0 , 0 ,,
      .1      .1
   214.2   222.2
      .1      .1
   214.2   222.2
BR Coef= 0 , 0 ,-1 ,1.25, 0 ,,,0.8192319,0,,2,222.2
WSPro=,,,, 1 ,,,, 0 ,,,, 0 ,,,,-1 ,-1 ,-1 , 0 , 0 , 0 , 0 , 0
BC Design=,, 0 ,, 0 ,,,,,,
BC Use User HTab Curves=0
BC User HTab FreeFlow(D)= 0

Type RM Length L Ch R = 1 ,126.65  ,25,25,25
BEGIN DESCRIPTION:
RICH CNTY FEMA XS: G
END DESCRIPTION:
#Sta/Elev= 19
       0   234.7     100   229.4     200   226.8     279     225     300   225.5
     301     224     400     223     426   222.7     500   221.3     600   220.8
     670   220.4     686   219.9     699   214.8     701   214.2     704   214.4
     720   219.2     997   220.2    1018   223.1    1084   234.7
#Mann= 3 , 0 , 0
       0      .1       0     686     .06       0     720      .1       0
#XS Ineff= 2 , 0
             686   222.2     720           222.2
Permanent Ineff=
       F       F
Bank Sta=686,720
XS Rating Curve= 0 ,0
Exp/Cntr=0.3,0.1

Type RM Length L Ch R = 1 ,126.45  ,325,325,325
#Sta/Elev= 19
       0   234.7     100   229.4     200   226.8     279     225     300   225.5
     301     224     400     223     426   222.7     500   221.3     600   220.8
     670   220.4     686   219.9     699   214.8     701   214.2     704   214.4
     720   219.2     997   220.2    1018   223.1    1084   234.7
#Mann= 3 , 0 , 0
       0      .1       0     686     .06       0     720      .1       0
Bank Sta=686,720
XS Rating Curve= 0 ,0
Exp/Cntr=0.3,0.1

Type RM Length L Ch R = 1 ,123.15  ,215,215,215
#Sta/Elev= 30
       0   228.3    25.7   228.3    26.2   228.8    44.5   228.7    46.8   227.3
   152.3   225.2   219.3   225.2   220.7   225.7   243.5   225.7   247.5   225.4
   305.9   224.5   306.9   224.9     372     225     390   224.7   391.6   223.7
   404.3   217.3   413.2   217.5   415.9     216     420   215.9   421.8   217.7
     429   219.7   482.1   220.1   500.8   220.7   531.3     221     592   221.1
   600.9   222.7   611.4   223.9   618.3   225.2   752.8   226.6   761.5   229.7
#Mann= 3 , 0 , 0
       0      .1       0   391.6     .06       0   482.1      .1       0
Bank Sta=391.6,482.1
XS Rating Curve= 0 ,0
Exp/Cntr=0.3,0.1

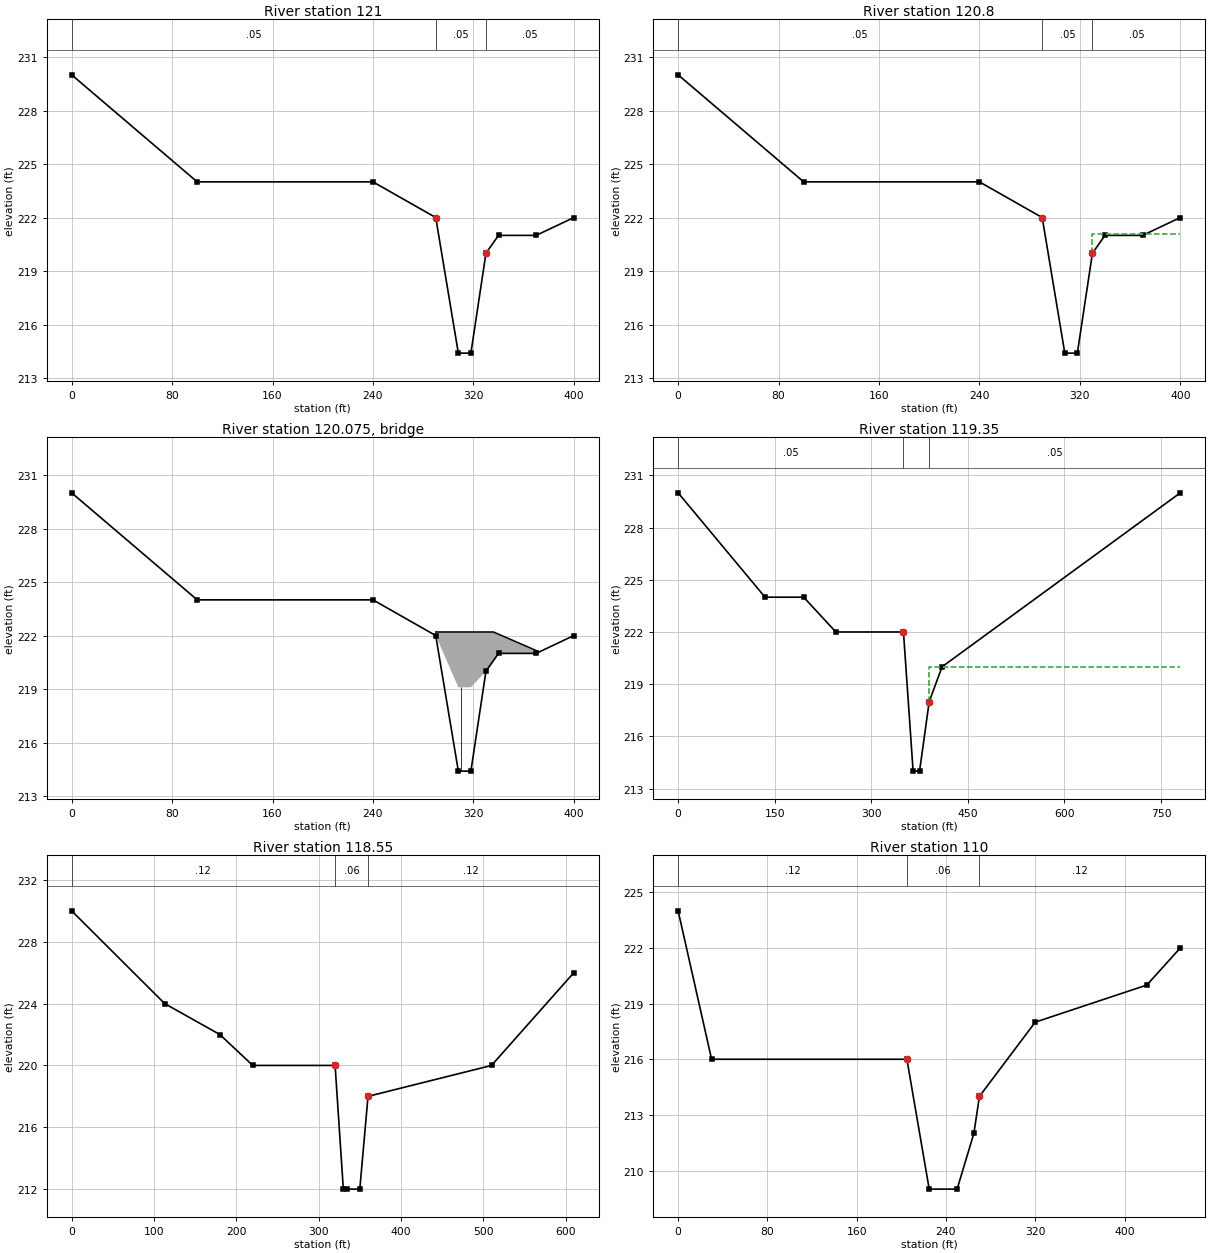
Type RM Length L Ch R = 1 ,121     ,20,20,20
#Sta/Elev= 10
       0     230     100     224     240     224     290     222     308   214.4
     318   214.4     330     220     340     221     370     221     400     222
#Mann= 3 , 0 , 0
       0     .05       0     290     .05       0     330     .05       0
Bank Sta=290,330
XS Rating Curve= 0 ,0
Exp/Cntr=0.4,0.2

Type RM Length L Ch R = 1 ,120.8   ,145,145,145
BEGIN DESCRIPTION:
RICH CNTY FEMA XS: F
END DESCRIPTION:
#Sta/Elev= 10
       0     230     100     224     240     224     290     222     308   214.4
     318   214.4     330     220     340     221     370     221     400     222
#Mann= 3 , 0 , 0
       0     .05       0     290     .05       0     330     .05       0
#XS Ineff= 2 , 0
             290   221.1     330           221.1
Permanent Ineff=
       F       F
Bank Sta=290,330
XS Rating Curve= 0 ,0
Exp/Cntr=0.4,0.2

Type RM Length L Ch R = 3 ,120.075 ,,,
BEGIN DESCRIPTION:
Bridge #7
END DESCRIPTION:
Bridge Culvert--1,0,-1,-1, 0
Deck Dist Width WeirC Skew NumUp NumDn MinLoCord MaxHiCord MaxSubmerge Is_Ogee
0.25,144.5,2.8,0, 6, 7, 221.1, , 0.98, 0, 0,0,,
     290     290     330     330     336     372
   222.2   222.2   222.2   222.2   222.2   221.1
       0   219.1   219.1       0       0       0
     336     350     350     372     390     390     410
   222.2 221.772 221.772   221.1   221.1   221.1   221.1
     214     214   219.1   219.1   219.1       0       0
Pier Skew, UpSta & Num, DnSta & Num=  ,310, 2 ,370, 2 , 0 , 0 , 0 ,,
     .01     .01
   214.4   219.1
     .01     .01
     214   219.1
BR Coef= 0 , 0 ,-1 ,1.05, 0 ,,,0.8391814,0,,2,219.1
WSPro=,,,, 1 ,,,, 0 ,,,, 0 ,,,,-1 ,-1 ,-1 , 0 , 0 , 0 , 0 , 0
BC Design=,, 0 ,, 0 ,,,,,,
BC Use User HTab Curves=0
BC User HTab FreeFlow(D)= 0

Type RM Length L Ch R = 1 ,119.35  ,80,80,80
#Sta/Elev= 10
       0     230     135     224     195     224     245     222     350     222
     365     214     375     214     390     218     410     220     780     230
#Mann= 3 , 0 , 0
       0     .05       0     350     .05       0     390     .05       0
#XS Ineff= 2 , 0
             350     220     390             220
Permanent Ineff=
       F       F
Bank Sta=350,390
XS Rating Curve= 0 ,0
Exp/Cntr=0.4,0.2

Type RM Length L Ch R = 1 ,118.55  ,855,855,855
BEGIN DESCRIPTION:
RICH CNTY FEMA XS: E
END DESCRIPTION:
#Sta/Elev= 11
       0     230     113     224     180     222     220     220     320     220
     330     212     335     212     350     212     360     218     510     220
     610     226
#Mann= 3 , 0 , 0
       0     .12       0     320     .06       0     360     .12       0
Bank Sta=320,360
XS Rating Curve= 0 ,0
Exp/Cntr=0.3,0.1

Type RM Length L Ch R = 1 ,110     ,425,425,425
#Sta/Elev= 10
       0     224      30     216     205     216     225     209     250     209
     265     212     270     214     320     218     420     220     450     222
#Mann= 3 , 0 , 0
       0     .12       0     205     .06       0     270     .12       0
Bank Sta=205,270
XS Rating Curve= 0 ,0
Exp/Cntr=0.3,0.1

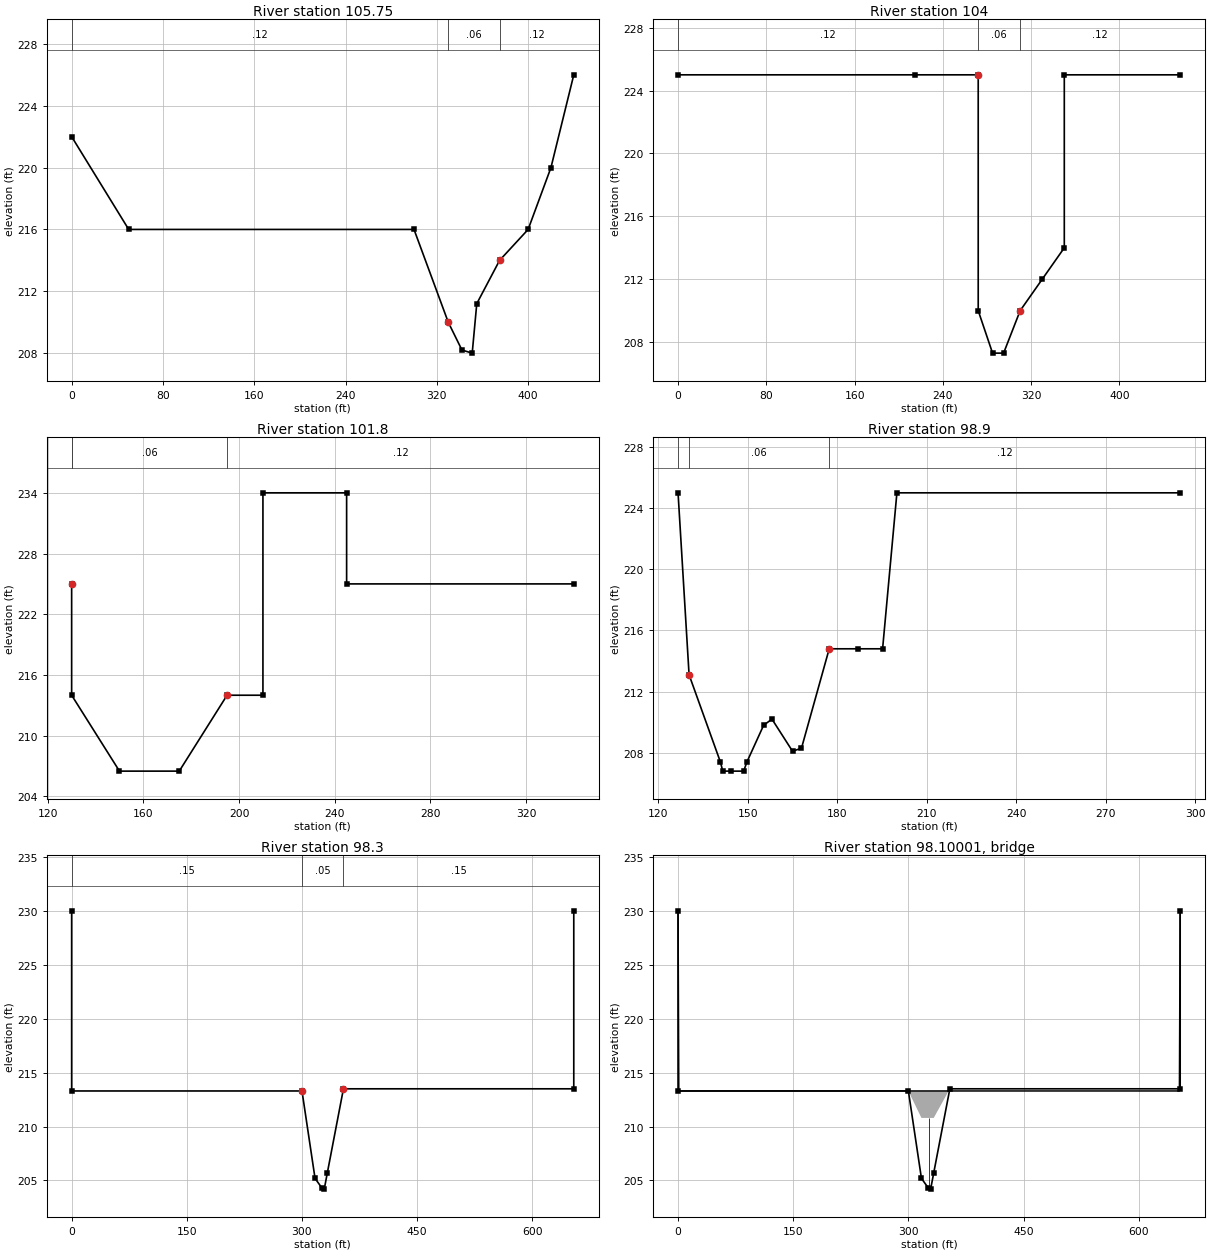
Type RM Length L Ch R = 1 ,105.75  ,175,175,175
BEGIN DESCRIPTION:
RICH CNTY FEMA XS: D
END DESCRIPTION:
#Sta/Elev= 11
       0     222      50     216     300     216     330     210     342   208.2
     351     208     355   211.2     375     214     400     216     420     220
     440     226
#Mann= 3 , 0 , 0
       0     .12       0     330     .06       0     375     .12       0
Bank Sta=330,375
XS Rating Curve= 0 ,0
Exp/Cntr=0.3,0.1

Type RM Length L Ch R = 1 ,104     ,220,220,220
#Sta/Elev= 11
       0     225     215     225     272     225     272     210     285   207.3
     295   207.3     310     210     330     212     350     214     350     225
     455     225
#Mann= 3 , 0 , 0
       0     .12       0     272     .06       0     310     .12       0
Bank Sta=272,310
XS Rating Curve= 0 ,0
Exp/Cntr=0.3,0.1

Type RM Length L Ch R = 1 ,101.8   ,290,290,290
BEGIN DESCRIPTION:
RICH CNTY FEMA XS: C
END DESCRIPTION:
#Sta/Elev= 10
     130     225     130     214     150   206.5     175   206.5     195     214
     210     214     210     234     245     234     245     225     340     225
#Mann= 3 , 0 , 0
     130     .12       0     130     .06       0     195     .12       0
Bank Sta=130,195
XS Rating Curve= 0 ,0
Exp/Cntr=0.3,0.1

Type RM Length L Ch R = 1 ,98.9    ,60,60,60
#Sta/Elev= 16
   126.6     225   130.3   213.1   140.8   207.4   141.6   206.8   144.5   206.8
   148.6   206.8   149.7   207.4   155.3   209.8   158.1   210.2     165   208.1
     168   208.3   177.3   214.8     187   214.8   195.2   214.8     200     225
     295     225
#Mann= 3 , 0 , 0
   126.6     .12       0   130.3     .06       0   177.3     .12       0
Bank Sta=130.3,177.3
XS Rating Curve= 0 ,0
Exp/Cntr=0.3,0.1

Type RM Length L Ch R = 1 ,98.3    ,40,40,40
#Sta/Elev= 10
       0     230       0   213.3     300   213.3     317   205.2     326   204.3
     329   204.2     333   205.7     354   213.5     654   213.5     654     230
#Mann= 3 , 0 , 0
       0     .15       0     300     .05       0     354     .15       0
#XS Ineff= 2 , 0
             300   213.3     354           213.3
Permanent Ineff=
       F       F
Bank Sta=300,354
XS Rating Curve= 0 ,0
Exp/Cntr=0.5,0.3

Type RM Length L Ch R = 3 ,98.10001,,,
BEGIN DESCRIPTION:
Bridge #6
END DESCRIPTION:
Bridge Culvert--1,0,-1,-1, 0
Deck Dist Width WeirC Skew NumUp NumDn MinLoCord MaxHiCord MaxSubmerge Is_Ogee
0.25,39.5,2.8,0, 9, 9, 213.3, , 0.98, 0, 0,0,,
       0       1     300     300     354     354     600     653     654
     230   213.3   213.3   213.3   213.3   213.3   213.3   213.3     230
   204.2   204.2   204.2   210.8   210.8   204.2   204.2   204.2   204.2
       0       1     300     300     354     354     600     653     654
     230   213.3   213.3   213.3   213.3   213.3   213.3   213.3     230
   204.2   204.2   204.2   210.8   210.8   204.2   204.2   204.2   204.2
Pier Skew, UpSta & Num, DnSta & Num=  ,327, 2 ,327, 2 , 0 , 0 , 0 ,,
       1       1
   204.2   210.8
       1       1
   204.2   210.8
BR Coef= 0 , 0 ,-1 ,0.9, 0 ,,,0.7352146,0,,2,210.8
WSPro=,,,, 1 ,,,, 0 ,,,, 0 ,,,,-1 ,-1 ,-1 , 0 , 0 , 0 , 0 , 0
BC Design=,, 0 ,, 0 ,,,,,,
BC Use User HTab Curves=0
BC User HTab FreeFlow(D)= 0

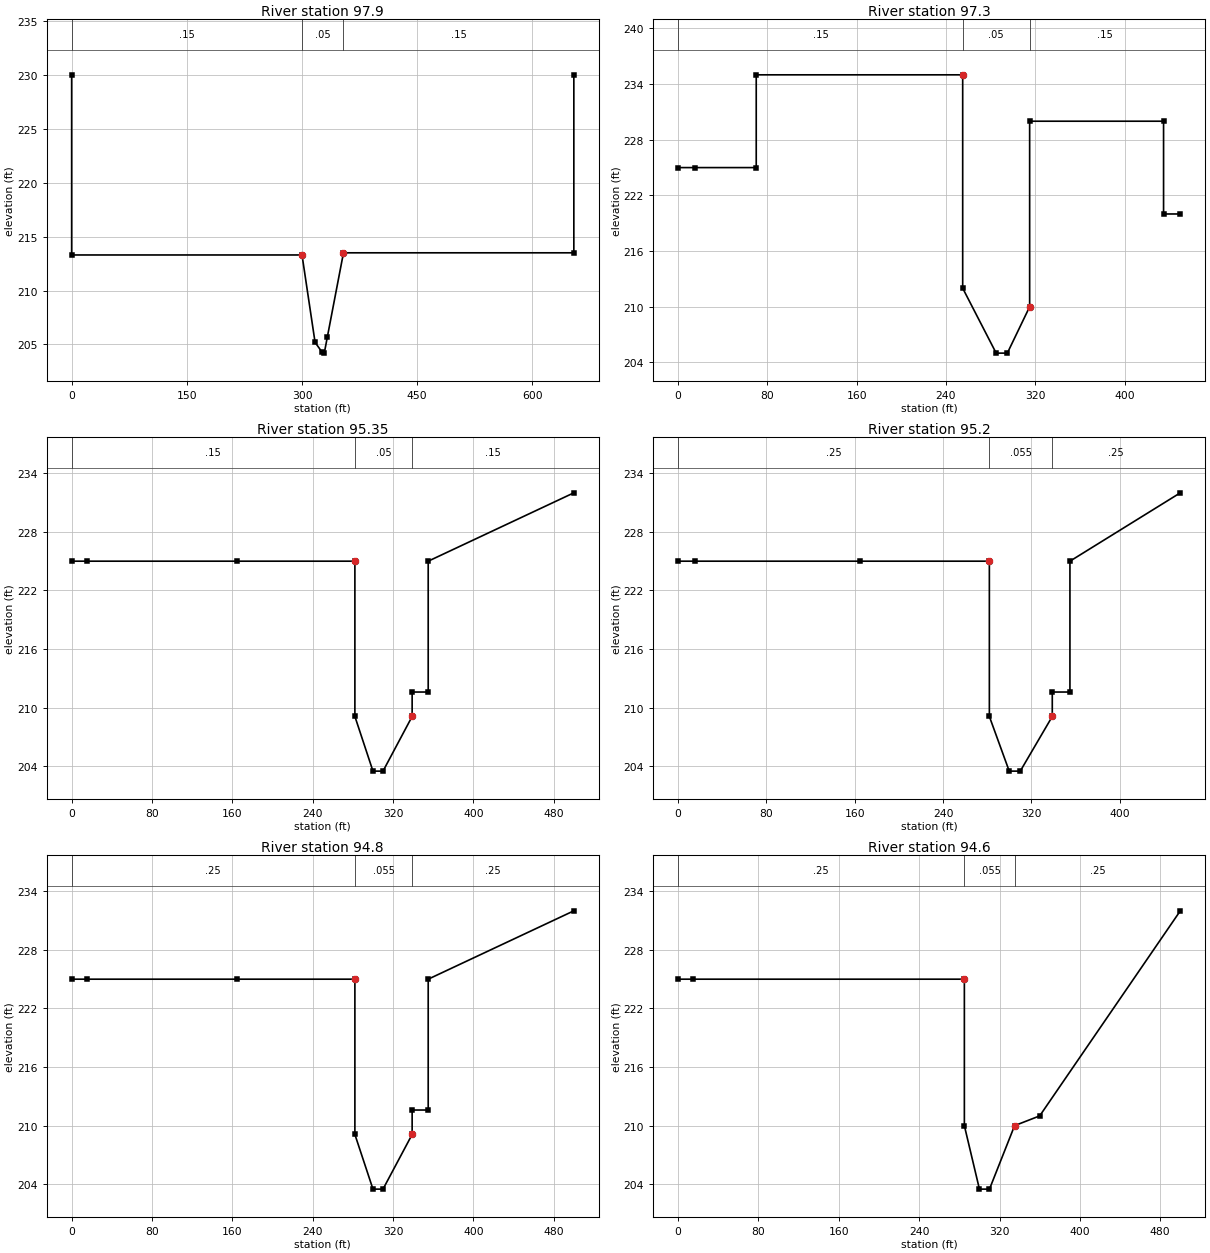
Type RM Length L Ch R = 1 ,97.9    ,60,60,60
#Sta/Elev= 10
       0     230       0   213.3     300   213.3     317   205.2     326   204.3
     329   204.2     333   205.7     354   213.5     654   213.5     654     230
#Mann= 3 , 0 , 0
       0     .15       0     300     .05       0     354     .15       0
#XS Ineff= 2 , 0
             300   210.8     354           210.8
Permanent Ineff=
       F       F
Bank Sta=300,354
XS Rating Curve= 0 ,0
Exp/Cntr=0.5,0.3

Type RM Length L Ch R = 1 ,97.3    ,195,195,195
#Sta/Elev= 13
       0     225      15     225      70     225      70     235     255     235
     255     212     285     205     295     205     315     210     315     230
     435     230     435     220     450     220
#Mann= 3 , 0 , 0
       0     .15       0     255     .05       0     315     .15       0
Bank Sta=255,315
XS Rating Curve= 0 ,0
Exp/Cntr=0.5,0.3

Type RM Length L Ch R = 1 ,95.35   ,15,15,15
#Sta/Elev= 12
       0     225      15     225     165     225     282     225     282   209.1
     300   203.5     310   203.5     339   209.1     339   211.6     355   211.6
     355     225     500     232
#Mann= 3 , 0 , 0
       0     .15       0     282     .05       0     339     .15       0
Bank Sta=282,339
XS Rating Curve= 0 ,0
Exp/Cntr=0.5,0.3

Type RM Length L Ch R = 1 ,95.2    ,40,40,40
#Sta/Elev= 12
       0     225      15     225     165     225     282     225     282   209.1
     300   203.5     310   203.5     339   209.1     339   211.6     355   211.6
     355     225     455     232
#Mann= 3 , 0 , 0
       0     .25       0     282    .055       0     339     .25       0
#XS Lid=4
     165     212       0     282   210.6   209.1     339   211.6   209.1
     455     212       0
Bank Sta=282,339
XS Rating Curve= 0 ,0
Exp/Cntr=0.5,0.3

Type RM Length L Ch R = 1 ,94.8    ,20,20,20
BEGIN DESCRIPTION:
RICH CNTY FEMA XS: B
END DESCRIPTION:
#Sta/Elev= 12
       0     225      15     225     165     225     282     225     282   209.1
     300   203.5     310   203.5     339   209.1     339   211.6     355   211.6
     355     225     500     232
#Mann= 3 , 0 , 0
       0     .25       0     282    .055       0     339     .25       0
Bank Sta=282,339
XS Rating Curve= 0 ,0
Exp/Cntr=0.5,0.3

Type RM Length L Ch R = 1 ,94.6    ,130,130,130
BEGIN DESCRIPTION:
LEX CNTY FEMA XS: O / RICH CNTY FEMA XS: A
END DESCRIPTION:
#Sta/Elev= 9
       0     225      15     225     285     225     285     210     300   203.5
     310   203.5     335     210     360     211     500     232
#Mann= 3 , 0 , 0
       0     .25       0     285    .055       0     335     .25       0
Bank Sta=285,335
XS Rating Curve= 0 ,0
Exp/Cntr=0.3,0.1

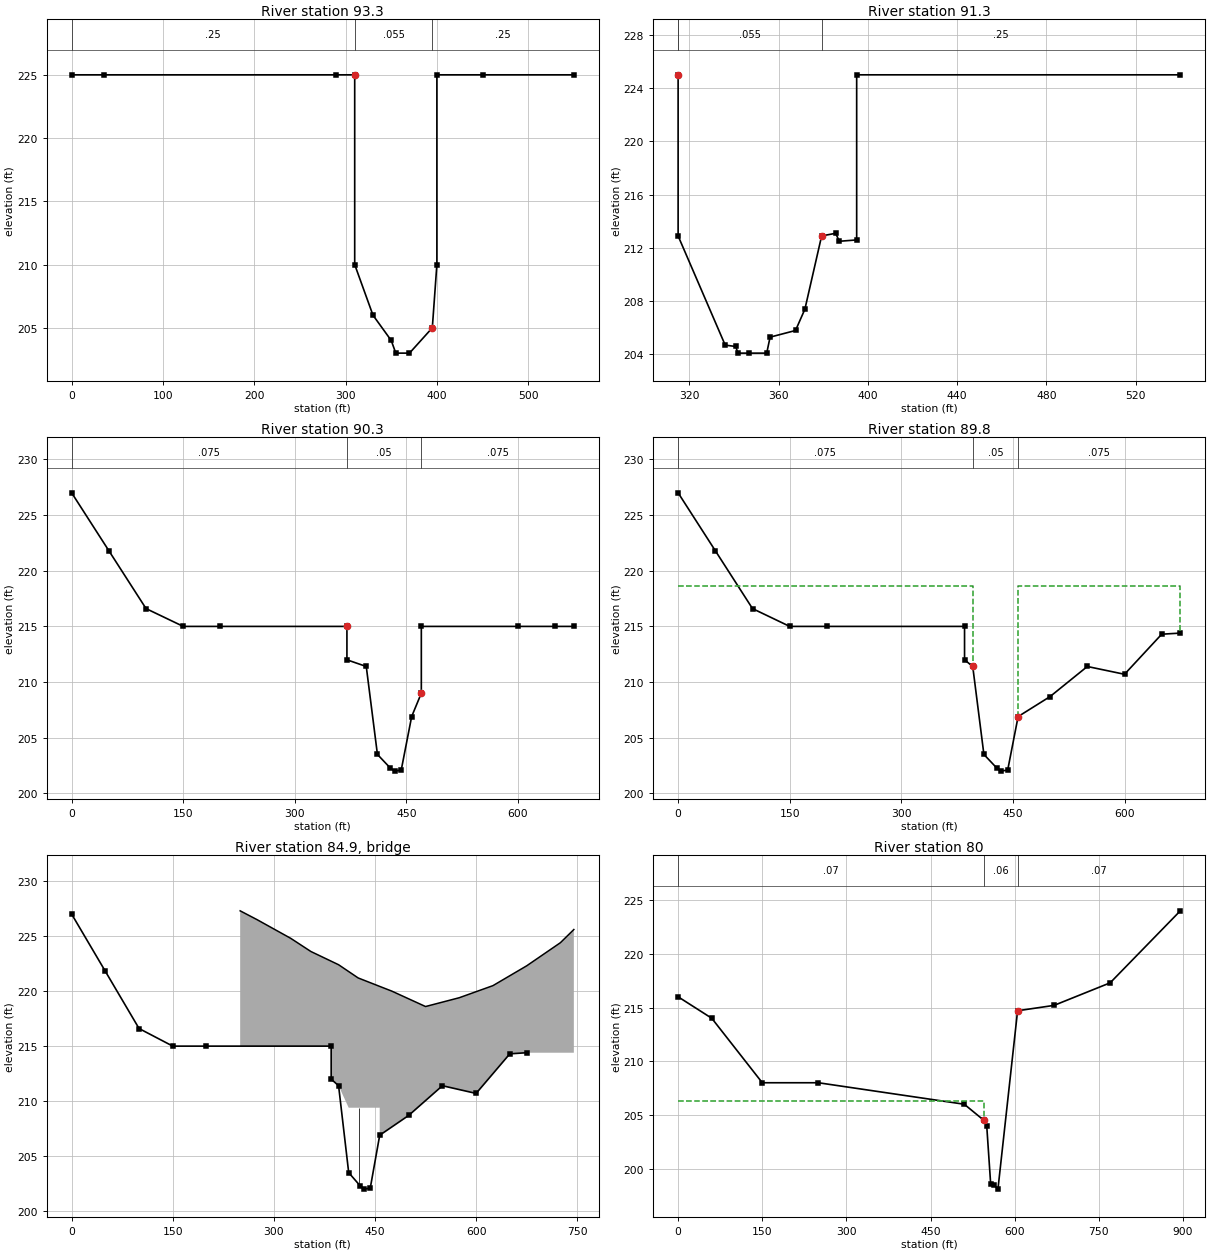
Type RM Length L Ch R = 1 ,93.3    ,200,200,200
#Sta/Elev= 14
       0     225      35     225     290     225     310     225     310     210
     330     206     350     204     355     203     370     203     395     205
     400     210     400     225     450     225     550     225
#Mann= 3 , 0 , 0
       0     .25       0     310    .055       0     395     .25       0
Bank Sta=310,395
XS Rating Curve= 0 ,0
Exp/Cntr=0.3,0.1

Type RM Length L Ch R = 1 ,91.3    ,100,100,100
#Sta/Elev= 16
     315     225     315   212.9   336.1   204.7   340.8   204.6   341.8   204.1
   346.6   204.1   354.7   204.1   356.2   205.3   367.6   205.8   371.8   207.4
   379.3   212.9   385.6   213.1   387.2   212.5     395   212.6     395     225
     540     225
#Mann= 3 , 0 , 0
     315     .25       0     315    .055       0   379.3     .25       0
Bank Sta=315,379.3
XS Rating Curve= 0 ,0
Exp/Cntr=0.3,0.1

Type RM Length L Ch R = 1 ,90.3    ,50,50,50
#Sta/Elev= 18
       0     227      50   221.8     100   216.6     150     215     200     215
     370     215     370     212     396   211.4     411   203.5     428   202.3
     434     202     443   202.1     457   206.9     470     209     470     215
     600     215     650     215     675     215
#Mann= 3 , 0 , 0
       0    .075       0     370     .05       0     470    .075       0
Bank Sta=370,470
XS Rating Curve= 0 ,0
Exp/Cntr=0.5,0.3

Type RM Length L Ch R = 1 ,89.8    ,980,980,980
#Sta/Elev= 18
       0     227      50   221.8     100   216.6     150     215     200     215
     385     215     385     212     396   211.4     411   203.5     428   202.3
     434     202     443   202.1     457   206.9     500   208.7     550   211.4
     600   210.7     650   214.3     675   214.4
#Mann= 3 , 0 , 0
       0    .075       0     396     .05       0     457    .075       0
#XS Ineff= 2 , 0
             396   218.6     457           218.6
Permanent Ineff=
       F       F
Bank Sta=396,457
XS Rating Curve= 0 ,0
Exp/Cntr=0.5,0.3

Type RM Length L Ch R = 3 ,84.9    ,,,
BEGIN DESCRIPTION:
Bridge #5
END DESCRIPTION:
Bridge Culvert--1,0,-1,-1, 0
Deck Dist Width WeirC Skew NumUp NumDn MinLoCord MaxHiCord MaxSubmerge Is_Ogee
0.25,979.5,2.8,0, 16, 17, 218.6, , 0.98, 0, 0,0,,
     250     275     325     355     396     396     425     457     457     475
     525     575     625     675     725     745
   227.3   226.5   224.8   223.6   222.4   222.4   221.2  220.43  220.43     220
   218.6   219.4   220.5   222.3   224.4   225.6
     180     180     180     180     180   209.4   209.4   209.4     180     180
     180     180     180     180     180     180
     250     275     325     355     395     425     475     525     545     545
     575     605     605     625     675     725     745
   227.3   226.5   224.8   223.6   222.4   221.2     220   218.6  218.92  218.92
   219.4  220.06  220.06   220.5   222.3   224.4   225.6
     180     180     180     180     180     180     180     180     180   209.4
   209.4   209.4     180     180     180     180     180
Pier Skew, UpSta & Num, DnSta & Num=  ,426.5, 2 ,575, 2 , 0 , 0 , 0 ,,
       1       1
     202   209.4
       1       1
   198.1   209.4
BR Coef= 0 , 0 ,-1 ,1.25, 0 ,,,0.5504819,0,,2,209.4
WSPro=,,,, 1 ,,,, 0 ,,,, 0 ,,,,-1 ,-1 ,-1 , 0 , 0 , 0 , 0 , 0
BC Design=,, 0 ,, 0 ,,,,,,
BC Use User HTab Curves=0
BC User HTab FreeFlow(D)= 0

Type RM Length L Ch R = 1 ,80      ,120,120,120
BEGIN DESCRIPTION:
LEX CNTY FEMA XS: N
END DESCRIPTION:
#Sta/Elev= 14
       0     216      60     214     150     208     250     208     510     206
     545   204.5     550     204     557   198.6     563   198.5     570   198.1
     605   214.7     670   215.2     770   217.3     895     224
#Mann= 3 , 0 , 0
       0     .07       0     545     .06       0     605     .07       0
#XS Ineff= 2 , 0
             545   206.3     605           206.3
Permanent Ineff=
       F       F
Bank Sta=545,605
XS Rating Curve= 0 ,0
Exp/Cntr=0.5,0.1

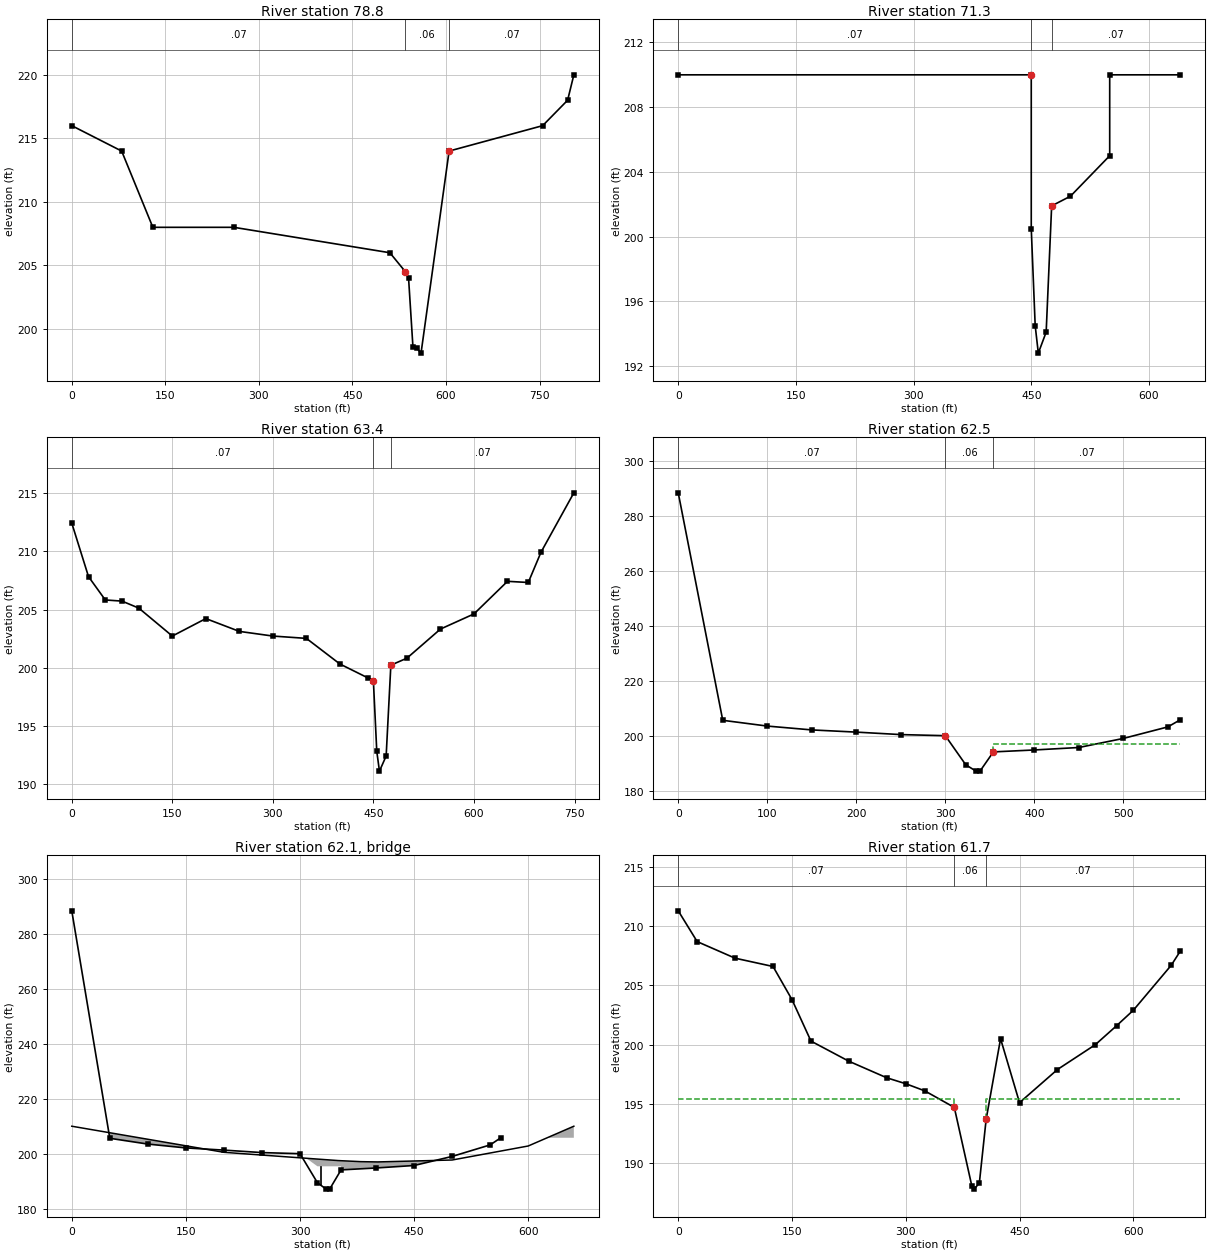
Type RM Length L Ch R = 1 ,78.8    ,750,750,750
#Sta/Elev= 14
       0     216      80     214     130     208     260     208     510     206
     535   204.5     540     204     547   198.6     553   198.5     560   198.1
     605     214     755     216     795     218     805     220
#Mann= 3 , 0 , 0
       0     .07       0     535     .06       0     605     .07       0
Bank Sta=535,605
XS Rating Curve= 0 ,0
Exp/Cntr=0.5,0.1

Type RM Length L Ch R = 1 ,71.3    ,790,790,790
BEGIN DESCRIPTION:
LEX CNTY FEMA XS: M
END DESCRIPTION:
#Sta/Elev= 11
       0     210     450     210     450   200.5     455   194.5     459   192.8
     469   194.1     476   201.9     500   202.5     550     205     550     210
     640     210
#Mann= 3 , 0 , 0
       0     .07       0     450     .06       0     476     .07       0
Bank Sta=450,476
XS Rating Curve= 0 ,0
Exp/Cntr=0.5,0.1

Type RM Length L Ch R = 1 ,63.4    ,90,90,90
BEGIN DESCRIPTION:
LEX CNTY FEMA XS: L
END DESCRIPTION:
#Sta/Elev= 24
       0  212.43      25  207.83      50  205.83      75  205.73     100  205.13
     150  202.73     200  204.23     250  203.13     300  202.73     350  202.53
     400  200.33     442  199.13     450  198.83     455  192.83     459  191.13
     469  192.43     476  200.23     500  200.83     550  203.33     600  204.63
     650  207.43     681  207.33     700  209.93     749  215.03
#Mann= 3 , 0 , 0
       0     .07       0     450     .06       0     476     .07       0
Bank Sta=450,476
XS Rating Curve= 0 ,0
Exp/Cntr=0.5,0.1

Type RM Length L Ch R = 1 ,62.5    ,80,80,80
#Sta/Elev= 16
       0   288.4      50   205.6     100   203.5     150   202.1     200   201.3
     250   200.4     300     200     323   189.4     334   187.2     339   187.1
     354   194.1     400   194.8     450   195.7     500     199     550   203.2
     564   205.8
#Mann= 3 , 0 , 0
       0     .07       0     300     .06       0     354     .07       0
#XS Ineff= 2 , 0
             300     197     354             197
Permanent Ineff=
       F       F
Bank Sta=300,354
XS Rating Curve= 0 ,0
Exp/Cntr=0.5,0.3

Type RM Length L Ch R = 3 ,62.1    ,,,
BEGIN DESCRIPTION:
Bridge #4
END DESCRIPTION:
Bridge Culvert--1,0,-1,-1, 0
Deck Dist Width WeirC Skew NumUp NumDn MinLoCord MaxHiCord MaxSubmerge Is_Ogee
0.25,79.5,2.8,0, 12, 12, 197, , 0.98, 0, 0,0,,
       0     200     300     300     350     354     354     380     402     500
     600     660
     210   200.5   198.5   198.5   197.5197.4467197.4467   197.1     197   197.7
   202.8     210
   187.1   187.1   187.1   195.4   195.4   195.4   187.1   187.1   187.1   187.1
   187.1   187.1
       0     200     350     364     364     380     402     406     406     500
     600     660
     210   200.5   197.5197.3133197.3133   197.1     197197.0286197.0286   197.7
   202.8     210
   187.1   187.1   187.1   187.1   195.4   195.4   195.4   195.4   187.1   187.1
   187.1   187.1
Pier Skew, UpSta & Num, DnSta & Num=  ,327, 2 ,385, 2 , 0 , 0 , 0 ,,
       1       1
   187.1   195.4
       1       1
   187.8   195.4
BR Coef= 0 , 0 ,-1 ,1.25, 0 ,,,0.7312724,0,,2,195.4
WSPro=,,,, 1 ,,,, 0 ,,,, 0 ,,,,-1 ,-1 ,-1 , 0 , 0 , 0 , 0 , 0
BC Design=,, 0 ,, 0 ,,,,,,
BC Use User HTab Curves=0
BC User HTab FreeFlow(D)= 0

Type RM Length L Ch R = 1 ,61.7    ,50,50,50
#Sta/Elev= 23
       0   211.3      25   208.7      75   207.3     125   206.6     150   203.8
     175   200.3     225   198.6     275   197.2     300   196.7     325   196.1
     364   194.7     387   188.1     390   187.8     397   188.3     406   193.7
     425   200.5     450   195.1     500   197.9     550     200     578   201.6
     600   202.9     650   206.7     662   207.9
#Mann= 3 , 0 , 0
       0     .07       0     364     .06       0     406     .07       0
#XS Ineff= 2 , 0
             364   195.4     406           195.4
Permanent Ineff=
       F       F
Bank Sta=364,406
XS Rating Curve= 0 ,0
Exp/Cntr=0.5,0.3