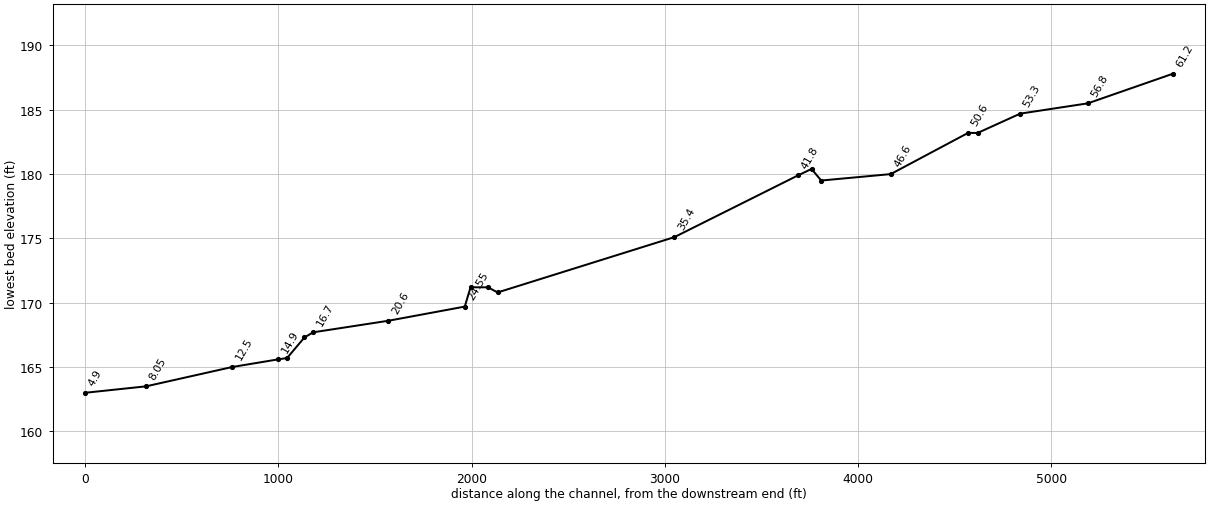
HEC-RAS study CCR_Stoop.prj: CCR_Stoop

--- CCR_Stoop.g01 (geometry) --- (continued)

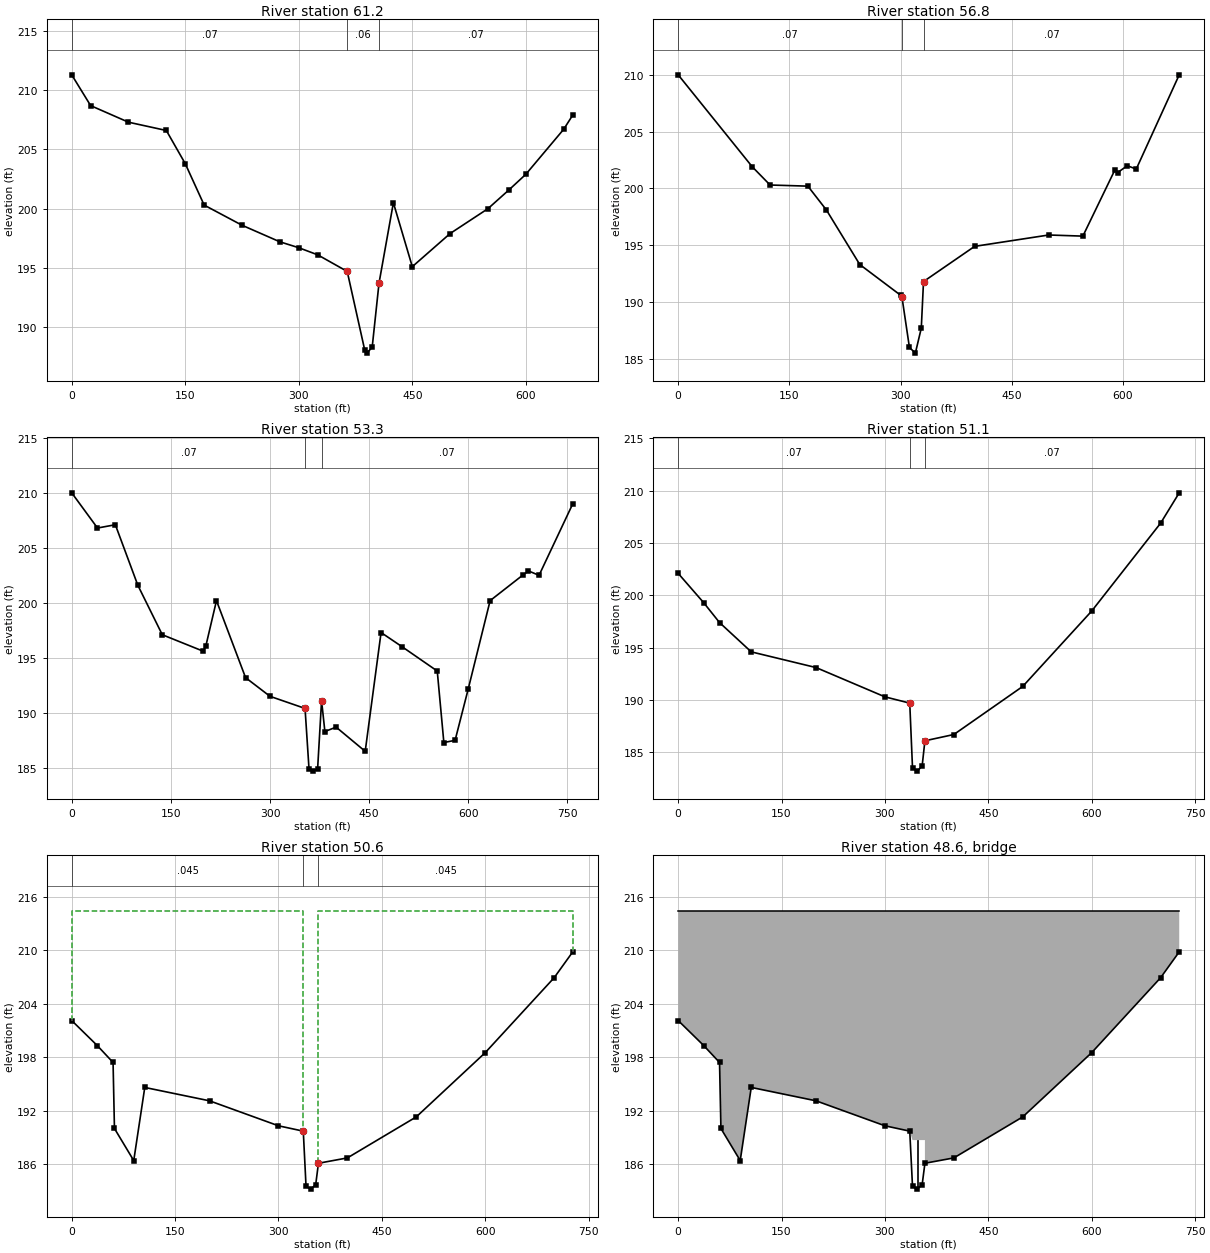
Type RM Length L Ch R = 1 ,61.2    ,440,440,440
BEGIN DESCRIPTION:
LEX CNTY FEMA XS: K
END DESCRIPTION:
#Sta/Elev= 23
       0   211.3      25   208.7      75   207.3     125   206.6     150   203.8
     175   200.3     225   198.6     275   197.2     300   196.7     325   196.1
     364   194.7     387   188.1     390   187.8     397   188.3     406   193.7
     425   200.5     450   195.1     500   197.9     550     200     578   201.6
     600   202.9     650   206.7     662   207.9
#Mann= 3 , 0 , 0
       0     .07       0     364     .06       0     406     .07       0
Bank Sta=364,406
XS Rating Curve= 0 ,0
Exp/Cntr=0.3,0.1

Type RM Length L Ch R = 1 ,56.8    ,350,350,350
BEGIN DESCRIPTION:
LEX CNTY FEMA XS: J
END DESCRIPTION:
#Sta/Elev= 20
       0     210     100   201.9     124   200.3     175   200.2     200   198.1
     245   193.3     300   190.6     302   190.4     312     186     320   185.5
     328   187.7     331   191.8     400   194.9     500   195.9     546   195.8
     589   201.6     593   201.4     606     202     618   201.7     676     210
#Mann= 3 , 0 , 0
       0     .07       0     302     .06       0     331     .07       0
Bank Sta=302,331
XS Rating Curve= 0 ,0
Exp/Cntr=0.3,0.1

Type RM Length L Ch R = 1 ,53.3    ,220,220,220
#Sta/Elev= 29
       0     210      39   206.8      66   207.1     100   201.6     137   197.1
     199   195.6     203   196.1     219   200.2     263   193.2     300   191.5
     353   190.4     359   184.9     365   184.7     372   184.9     378   191.1
     383   188.3     400   188.7     444   186.5     468   197.3     500     196
     553   193.8     563   187.3     580   187.5     600   192.2     633   200.2
     682   202.5     691   202.9     707   202.5     758     209
#Mann= 3 , 0 , 0
       0     .07       0     353     .06       0     378     .07       0
Bank Sta=353,378
XS Rating Curve= 0 ,0
Exp/Cntr=0.3,0.1

Type RM Length L Ch R = 1 ,51.1    ,50,50,50
BEGIN DESCRIPTION:
LEX CNTY FEMA XS: I
END DESCRIPTION:
#Sta/Elev= 16
       0   202.1      37   199.3      60   197.4     106   194.6     200   193.1
     300   190.3     336   189.7     340   183.5     347   183.2     354   183.7
     358   186.1     400   186.7     500   191.3     600   198.5     700   206.9
     727   209.8
#Mann= 3 , 0 , 0
       0     .07       0     336     .06       0     358     .07       0
Bank Sta=336,358
XS Rating Curve= 0 ,0
Exp/Cntr=0.3,0.1

Type RM Length L Ch R = 1 ,50.6    ,400,400,400
#Sta/Elev= 18
       0   202.1      37   199.3      60   197.4      62     190      90   186.4
     106   194.6     200   193.1     300   190.3     336   189.7     340   183.5
     347   183.2     354   183.7     358   186.1     400   186.7     500   191.3
     600   198.5     700   206.9     727   209.8
#Mann= 3 , 0 , 0
       0    .045       0     336   .0315       0     358    .045       0
#XS Ineff= 2 , 0
             336   214.4     358           214.4
Permanent Ineff=
       F       F
Bank Sta=336,358
XS Rating Curve= 0 ,0
Exp/Cntr=0.5,0.3

Type RM Length L Ch R = 3 ,48.6    ,,,
BEGIN DESCRIPTION:
Bridge #3
END DESCRIPTION:
Bridge Culvert--1,0,-1,-1, 0
Deck Dist Width WeirC Skew NumUp NumDn MinLoCord MaxHiCord MaxSubmerge Is_Ogee
0.25,399.5,2.8,0, 6, 6, 214.4, , 0.98, 0, 0,0,,
       0     336     336     358     358     727
   214.4   214.4   214.4   214.4   214.4   214.4
     180     180   188.7   188.7     180     180
       0     175     175     200     200     727
   214.4   214.4   214.4   214.4   214.4   214.4
     180     180   188.7   188.7     180     180
Pier Skew, UpSta & Num, DnSta & Num=  ,347, 2 ,187.5, 2 , 0 , 0 , 0 ,,
       2       2
   183.2   188.7
       2       2
     180   188.7
BR Coef= 0 , 0 ,-1 ,1.25, 0 ,,,0.7254763,0,,2,188.7
WSPro=,,,, 1 ,,,, 0 ,,,, 0 ,,,,-1 ,-1 ,-1 , 0 , 0 , 0 , 0 , 0
BC Design=,, 0 ,, 0 ,,,,,,
BC Use User HTab Curves=0
BC User HTab FreeFlow(D)= 0

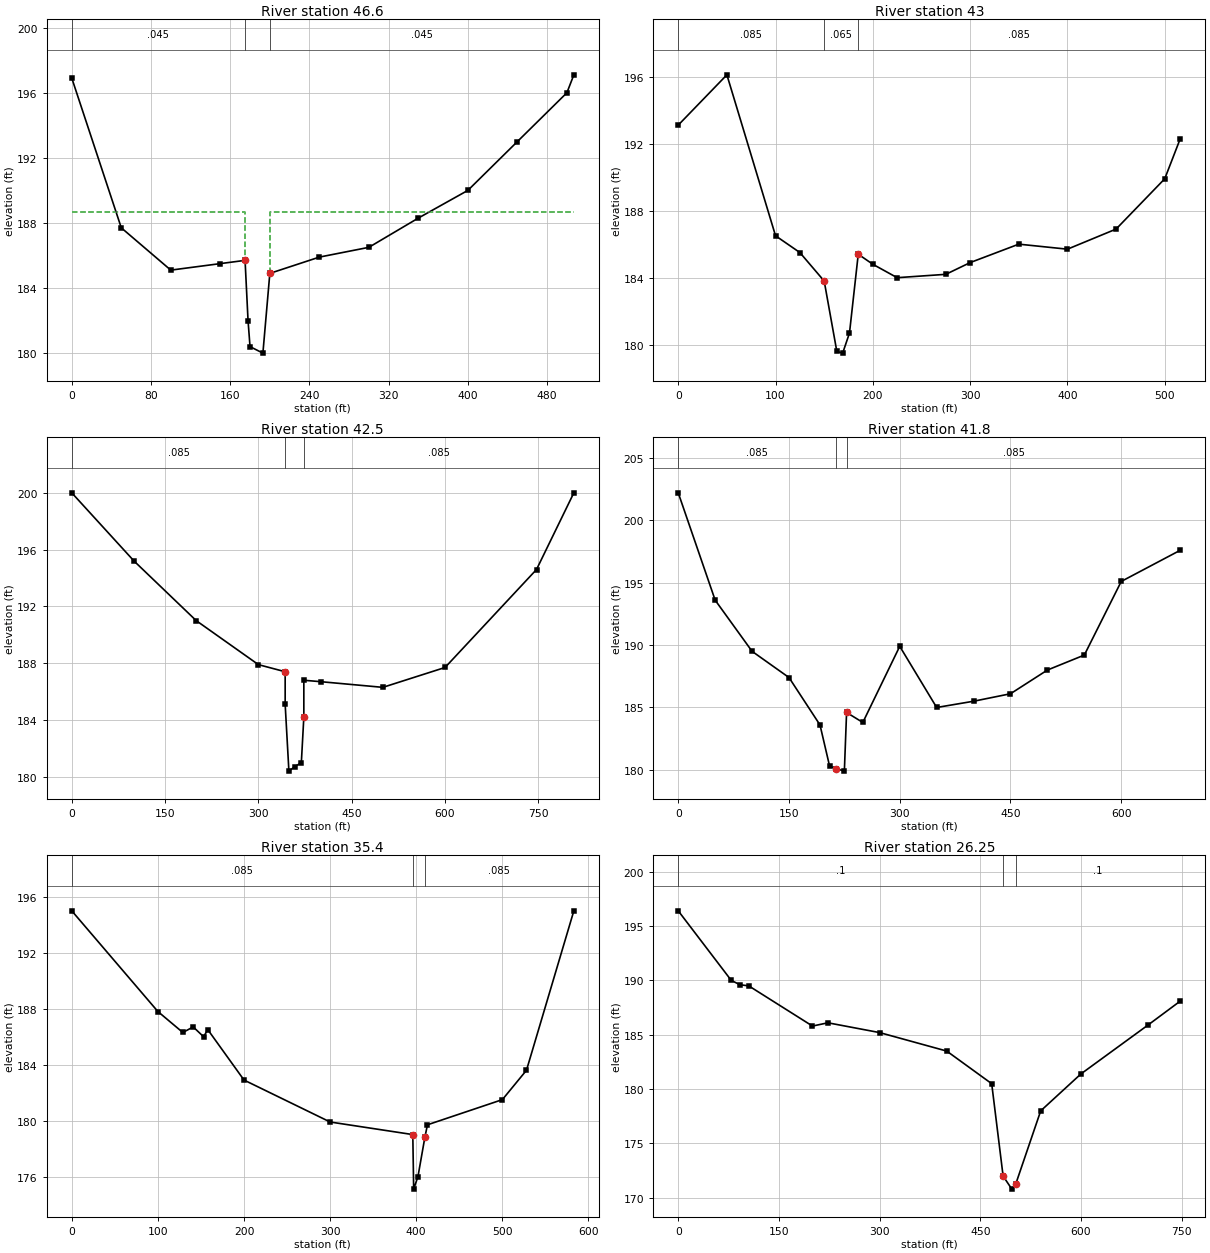
Type RM Length L Ch R = 1 ,46.6    ,360,360,360
BEGIN DESCRIPTION:
LEX CNTY FEMA XS: H
END DESCRIPTION:
#Sta/Elev= 16
       0   196.9      50   187.7     100   185.1     150   185.5     175   185.7
     178     182     180   180.4     193     180     200   184.9     250   185.9
     300   186.5     350   188.3     400     190     450     193     500     196
     507   197.1
#Mann= 3 , 0 , 0
       0    .045       0     175   .0315       0     200    .045       0
#XS Ineff= 2 , 0
             175   188.7     200           188.7
Permanent Ineff=
       F       F
Bank Sta=175,200
XS Rating Curve= 0 ,0
Exp/Cntr=0.5,0.3

Type RM Length L Ch R = 1 ,43      ,50,50,50
BEGIN DESCRIPTION:
LEX CNTY FEMA XS: G
END DESCRIPTION:
#Sta/Elev= 18
       0   193.1      50   196.1     100   186.5     125   185.5     150   183.8
     163   179.6     169   179.5     176   180.7     185   185.4     200   184.8
     225     184     275   184.2     300   184.9     350     186     400   185.7
     450   186.9     500   189.9     516   192.3
#Mann= 3 , 0 , 0
       0    .085       0     150    .065       0     185    .085       0
Bank Sta=150,185
XS Rating Curve= 0 ,0
Exp/Cntr=0.5,0.3

Type RM Length L Ch R = 1 ,42.5    ,70,70,70
BEGIN DESCRIPTION:
LEX CNTY FEMA XS: F
END DESCRIPTION:
#Sta/Elev= 16
       0     200     100   195.2     200     191     300   187.9     343   187.4
     343   185.1     349   180.4     358   180.7     369     181     373   184.2
     373   186.8     400   186.7     500   186.3     600   187.7     747   194.6
     807     200
#Mann= 3 , 0 , 0
       0    .085       0     343    .065       0     373    .085       0
#XS Lid=2
     343   187.4   185.1     373   186.8   184.2
Bank Sta=343,373
XS Rating Curve= 0 ,0
Exp/Cntr=0.5,0.3

Type RM Length L Ch R = 1 ,41.8    ,640,640,640
#Sta/Elev= 18
       0   202.2      50   193.6     100   189.5     150   187.4     192   183.6
     205   180.3     214   180.1     225   179.9     228   184.6     250   183.8
     300   189.9     350     185     400   185.5     450   186.1     500     188
     550   189.2     600   195.1     680   197.6
#Mann= 3 , 0 , 0
       0    .085       0     214    .055       0     228    .085       0
Bank Sta=214,228
XS Rating Curve= 0 ,0
Exp/Cntr=0.5,0.3

Type RM Length L Ch R = 1 ,35.4    ,915,915,915
BEGIN DESCRIPTION:
LEX CNTY FEMA XS: E
END DESCRIPTION:
#Sta/Elev= 16
       0     195     100   187.8     129   186.3     141   186.7     153     186
     158   186.5     200   182.9     300   179.9     396     179     397   175.1
     402     176     410   178.8     413   179.7     500   181.5     528   183.6
     583     195
#Mann= 3 , 0 , 0
       0    .085       0     396    .055       0     410    .085       0
Bank Sta=396,410
XS Rating Curve= 0 ,0
Exp/Cntr=0.3,0.1

Type RM Length L Ch R = 1 ,26.25   ,50,50,50
BEGIN DESCRIPTION:
LEX CNTY FEMA XS: D
END DESCRIPTION:
#Sta/Elev= 16
       0   196.4      79     190      92   189.6     105   189.5     200   185.8
     223   186.1     300   185.2     400   183.5     467   180.5     484     172
     497   170.8     503   171.3     540     178     600   181.4     700   185.9
     748   188.1
#Mann= 3 , 0 , 0
       0      .1       0     484    .055       0     503      .1       0
Bank Sta=484,503
XS Rating Curve= 0 ,0
Exp/Cntr=0.3,0.1

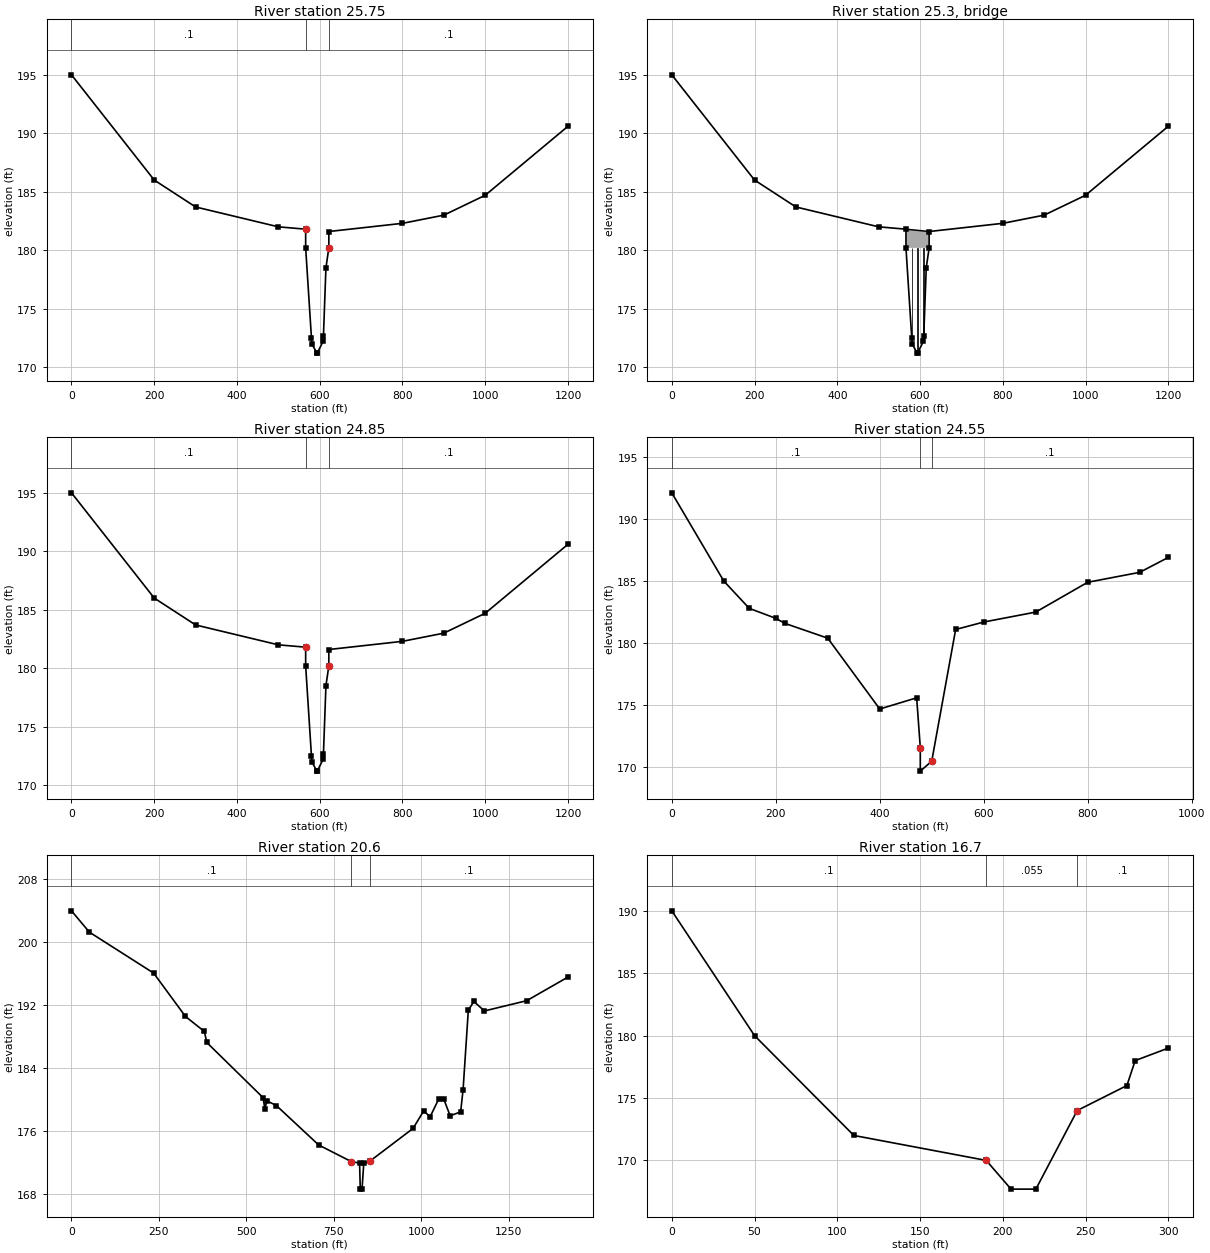
Type RM Length L Ch R = 1 ,25.75   ,90,90,90
#Sta/Elev= 19
       0     195     200     186     300   183.7     500     182     566   181.8
     566   180.2     580   172.5     581     172     593   171.2     594   171.2
     608   172.2     609   172.7     615   178.5     622   180.2     622   181.6
     800   182.3     900     183    1000   184.7    1200   190.6
#Mann= 3 , 0 , 0
       0      .1       0     566    .055       0     622      .1       0
Bank Sta=566,622
XS Rating Curve= 0 ,0
Exp/Cntr=0.3,0.1

Type RM Length L Ch R = 3 ,25.3    ,,,
BEGIN DESCRIPTION:
Bridge #2
END DESCRIPTION:
Bridge Culvert--1,0,-1,-1, 0
Deck Dist Width WeirC Skew NumUp NumDn MinLoCord MaxHiCord MaxSubmerge Is_Ogee
0.25,89.5,2.6,0, 2, 2, , , 0.98, 0, 0,0,,
     566     622
   181.8   181.6
   180.2   180.2
     566     622
   181.8   181.6
   180.2   180.2
Pier Skew, UpSta & Num, DnSta & Num=  ,580.5, 2 ,580.5, 2 , 0 , 0 , 0 ,,
       1       1
     170   180.2
       1       1
     170   180.2
Pier Skew, UpSta & Num, DnSta & Num=  ,593.5, 2 ,593.5, 2 , 0 , 0 , 0 ,,
       1       1
     170   180.2
       1       1
     170   180.2
Pier Skew, UpSta & Num, DnSta & Num=  ,608.5, 2 ,608.5, 2 , 0 , 0 , 0 ,,
       1       1
     170   180.2
       1       1
     170   180.2
BR Coef=-1 , 0 , 0 ,, 0 ,,,0.8,-1,,1,
WSPro=,,,, 1 ,,,, 0 ,,,, 0 ,,,,-1 ,-1 ,-1 , 0 , 0 , 0 , 0 , 0
BC Design=,, 0 ,, 0 ,,,,,,
BC Use User HTab Curves=0
BC User HTab FreeFlow(D)= 0

Type RM Length L Ch R = 1 ,24.85   ,30,30,30
#Sta/Elev= 19
       0     195     200     186     300   183.7     500     182     566   181.8
     566   180.2     580   172.5     581     172     593   171.2     594   171.2
     608   172.2     609   172.7     615   178.5     622   180.2     622   181.6
     800   182.3     900     183    1000   184.7    1200   190.6
#Mann= 3 , 0 , 0
       0      .1       0     566    .055       0     622      .1       0
Bank Sta=566,622
XS Rating Curve= 0 ,0
Exp/Cntr=0.3,0.1

Type RM Length L Ch R = 1 ,24.55   ,395,395,395
BEGIN DESCRIPTION:
LEX CNTY FEMA XS: C
END DESCRIPTION:
#Sta/Elev= 17
       0   192.1     100     185     149   182.8     200     182     217   181.6
     300   180.4     400   174.7     471   175.6     478   171.6     478   169.7
     500   170.5     546   181.1     600   181.7     700   182.5     800   184.9
     900   185.7     955   186.9
#Mann= 3 , 0 , 0
       0      .1       0     478    .055       0     500      .1       0
Bank Sta=478,500
XS Rating Curve= 0 ,0
Exp/Cntr=0.3,0.1

Type RM Length L Ch R = 1 ,20.6    ,390,390,390
#Sta/Elev= 30
       0   203.9      51   201.2     235     196     326   190.5     380   188.6
     387   187.2     548   180.2     553   178.8     559   179.8     586   179.2
     707   174.2     800   172.1     824   171.9     826   168.6     831   168.6
     836   171.9     855   172.2     977   176.3    1007   178.5    1026   177.8
    1050     180    1065     180    1083   177.9    1113   178.4    1120   181.2
    1135   191.3    1151   192.4    1181   191.2    1302   192.5    1420   195.5
#Mann= 3 , 0 , 0
       0      .1       0     800    .055       0     855      .1       0
Bank Sta=800,855
XS Rating Curve= 0 ,0
Exp/Cntr=0.3,0.1

Type RM Length L Ch R = 1 ,16.7    ,45,45,45
BEGIN DESCRIPTION:
LEX CNTY FEMA XS: B
END DESCRIPTION:
#Sta/Elev= 10
       0     190      50     180     110     172     190     170     205   167.7
     220   167.7     245     174     275     176     280     178     300     179
#Mann= 3 , 0 , 0
       0      .1       0     190    .055       0     245      .1       0
Bank Sta=190,245
XS Rating Curve= 0 ,0
Exp/Cntr=0.5,0.3

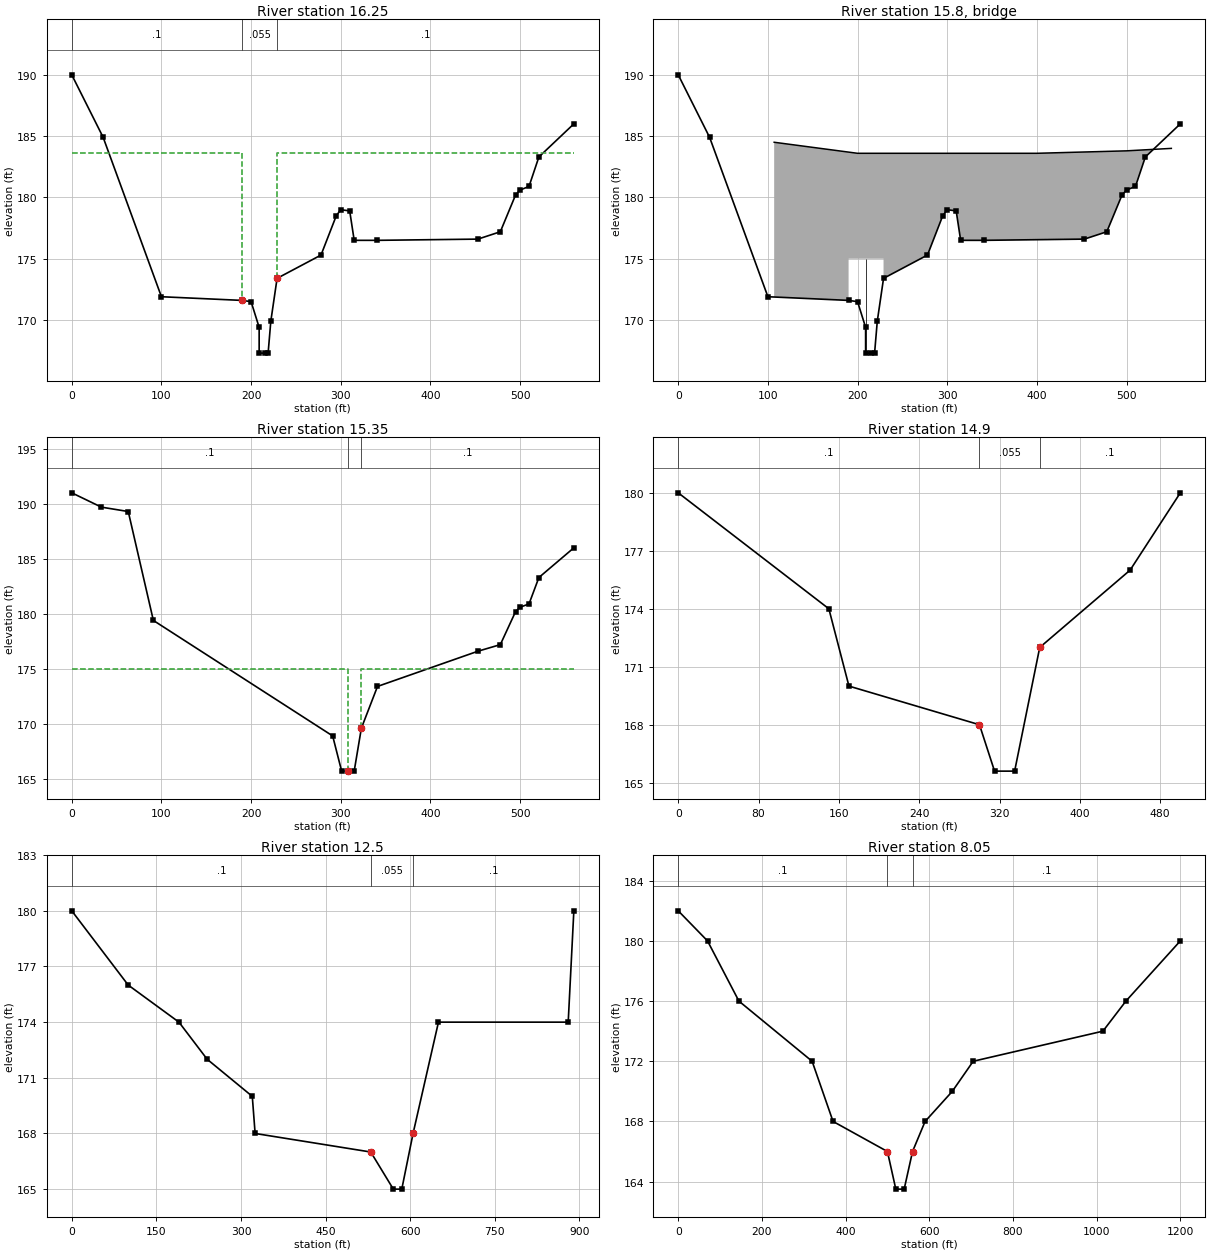
Type RM Length L Ch R = 1 ,16.25   ,90,90,90
#Sta/Elev= 24
       0     190      35   184.9     100   171.9     190   171.6     200   171.5
     209   169.4     209   167.3     215   167.3     219   167.3     222   169.9
     229   173.4     278   175.3     295   178.5     300     179     310   178.9
     315   176.5     341   176.5     453   176.6     478   177.2     495   180.2
     500   180.6     510   180.9     521   183.3     560     186
#Mann= 3 , 0 , 0
       0      .1       0     190    .055       0     229      .1       0
#XS Ineff= 2 , 0
             190   183.6     229           183.6
Permanent Ineff=
       F       F
Bank Sta=190,229
XS Rating Curve= 0 ,0
Exp/Cntr=0.5,0.3

Type RM Length L Ch R = 3 ,15.8    ,,,
BEGIN DESCRIPTION:
Bridge #1
END DESCRIPTION:
Bridge Culvert--1,0,-1,-1, 0
Deck Dist Width WeirC Skew NumUp NumDn MinLoCord MaxHiCord MaxSubmerge Is_Ogee
0.25,89.5,2.8,0, 9, 9, 183.6, , 0.98, 0, 0,0,,
     107     190     190     200     229     229     400     500     550
   184.5183.6968183.6968   183.6   183.6   183.6   183.6   183.8     184
   165.7   165.7     175     175     175   165.7   165.7   165.7   165.7
     107     200     308     308     323     323     400     500     550
   184.5   183.6   183.6   183.6   183.6   183.6   183.6   183.8     184
   165.7   165.7   165.7     175     175   165.7   165.7   165.7   165.7
Pier Skew, UpSta & Num, DnSta & Num=  ,209.5, 2 ,315.5, 2 , 0 , 0 , 0 ,,
     .01     .01
   167.3     175
     .01     .01
   165.7     175
BR Coef= 0 , 0 ,-1 ,1.5, 0 ,,,0.8873565,0,,2,175
WSPro=,,,, 1 ,,,, 0 ,,,, 0 ,,,,-1 ,-1 ,-1 , 0 , 0 , 0 , 0 , 0
BC Design=,, 0 ,, 0 ,,,,,,
BC Use User HTab Curves=0
BC User HTab FreeFlow(D)= 0

Type RM Length L Ch R = 1 ,15.35   ,45,45,45
#Sta/Elev= 17
       0     191      33   189.7      63   189.3      91   179.4     291   168.9
     301   165.7     308   165.7     315   165.7     323   169.6     341   173.4
     453   176.6     478   177.2     495   180.2     500   180.6     510   180.9
     521   183.3     560     186
#Mann= 3 , 0 , 0
       0      .1       0     308    .055       0     323      .1       0
#XS Ineff= 2 , 0
             308     175     323             175
Permanent Ineff=
       F       F
Bank Sta=308,323
XS Rating Curve= 0 ,0
Exp/Cntr=0.5,0.3

Type RM Length L Ch R = 1 ,14.9    ,240,240,240
BEGIN DESCRIPTION:
LEX CNTY FEMA XS: A
END DESCRIPTION:
#Sta/Elev= 9
       0     180     150     174     170     170     300     168     315   165.6
     335   165.6     360     172     450     176     500     180
#Mann= 3 , 0 , 0
       0      .1       0     300    .055       0     360      .1       0
Bank Sta=300,360
XS Rating Curve= 0 ,0
Exp/Cntr=0.3,0.1

Type RM Length L Ch R = 1 ,12.5    ,445,445,445
#Sta/Elev= 13
       0     180     100     176     190     174     240     172     320     170
     325     168     530     167     570     165     585     165     605     168
     650     174     880     174     890     180
#Mann= 3 , 0 , 0
       0      .1       0     530    .055       0     605      .1       0
Bank Sta=530,605
XS Rating Curve= 0 ,0
Exp/Cntr=0.3,0.1

Type RM Length L Ch R = 1 ,8.05    ,315,315,315
#Sta/Elev= 15
       0     182      70     180     145     176     320     172     370     168
     500     166     520   163.5     540   163.5     560     166     590     168
     655     170     705     172    1015     174    1070     176    1200     180
#Mann= 3 , 0 , 0
       0      .1       0     500    .055       0     560      .1       0
Bank Sta=500,560
XS Rating Curve= 0 ,0
Exp/Cntr=0.3,0.1

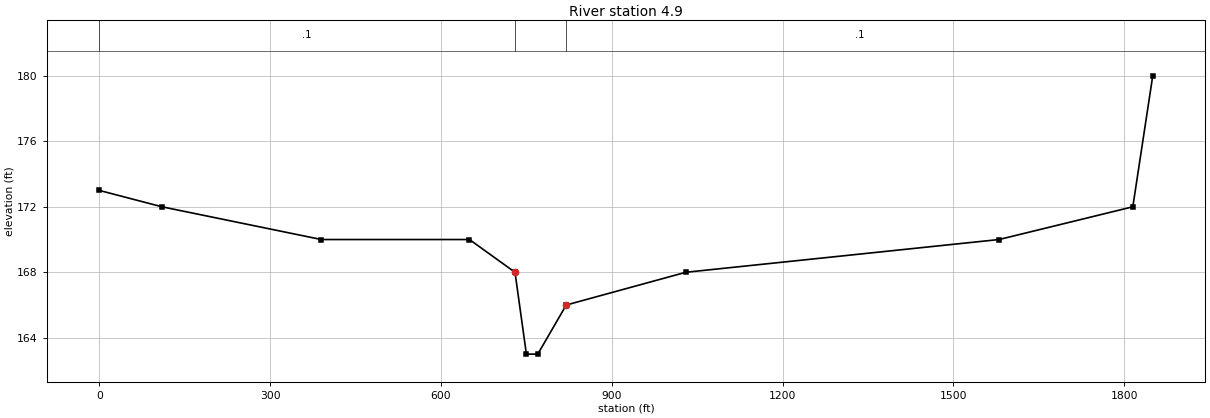
Type RM Length L Ch R = 1 ,4.9     ,0,0,0
#Sta/Elev= 12
       0     173     110     172     390     170     650     170     730     168
     750     163     770     163     820     166    1030     168    1580     170
    1815     172    1850     180
#Mann= 3 , 0 , 0
       0      .1       0     730    .055       0     820      .1       0
Bank Sta=730,820
XS Rating Curve= 0 ,0
Exp/Cntr=0.3,0.1

Chan Stop Cuts=-1
Use User Specified Reach Order=0
Composite Channel Slope=5

--- CCR_Stoop.g02 (geometry) ---

Geom Title=Natural
Program Version=4.10
BEGIN GEOM DESCRIPTION:
Lexington County portion of the model corrected.  Anticipate updated Richland County model.  Will combine once received.
END GEOM DESCRIPTION:

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
River Reach=Stoop Creek     ,Stoop Creek

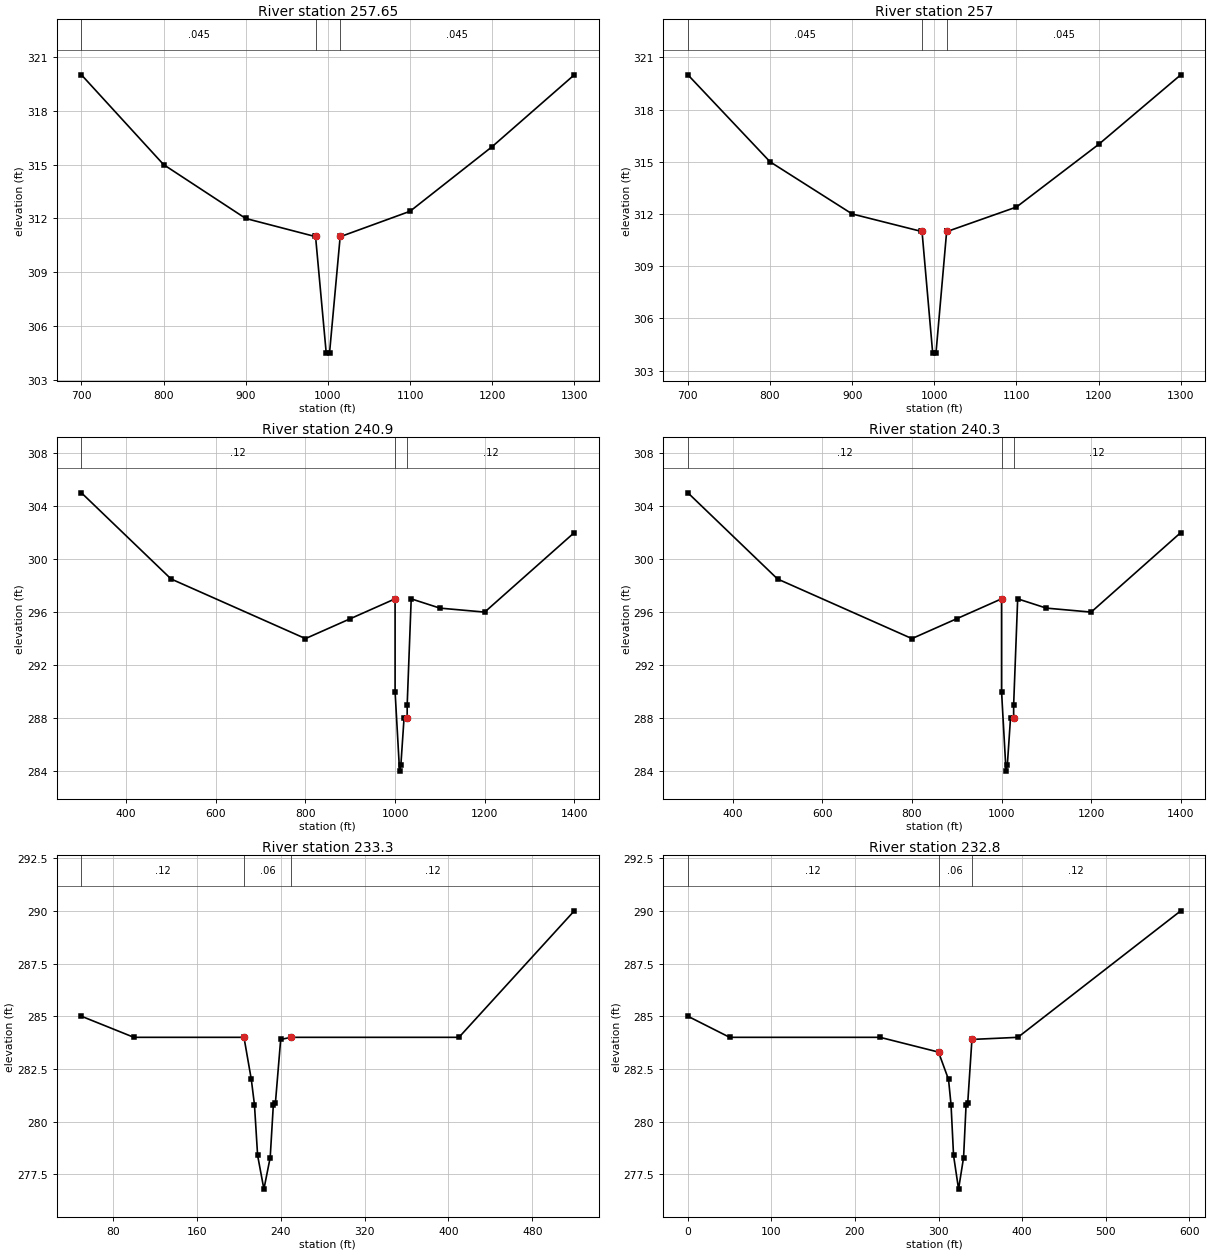
Type RM Length L Ch R = 1 ,257.65  ,65,65,65
#Sta/Elev= 12
     700     320     800     315     900     312     984     311     985     311
     998   304.5    1002   304.5    1015     311    1016     311    1100   312.4
    1200     316    1300     320
#Mann= 3 , 0 , 0
     700    .045       0     985   .0315       0    1015    .045       0
Bank Sta=985,1015
XS Rating Curve= 0 ,0
Exp/Cntr=0.5,0.3

Type RM Length L Ch R = 1 ,257     ,35,35,35
#Sta/Elev= 12
     700     320     800     315     900     312     984     311     985     311
     998     304    1002     304    1015     311    1016     311    1100   312.4
    1200     316    1300     320
#Mann= 3 , 0 , 0
     700    .045       0     985   .0315       0    1015    .045       0
Bank Sta=985,1015
XS Rating Curve= 0 ,0
Exp/Cntr=0.5,0.3

Type RM Length L Ch R = 1 ,240.9   ,60,60,60
#Sta/Elev= 15
     300     305     500   298.5     800     294     900   295.5    1000     297
    1000     290    1010     284    1013   284.5    1020     288    1027     288
    1027     289    1036     297    1100   296.3    1200     296    1400     302
#Mann= 3 , 0 , 0
     300     .12       0    1000     .06       0    1027     .12       0
Bank Sta=1000,1027
XS Rating Curve= 0 ,0
Exp/Cntr=0.3,0.1

Type RM Length L Ch R = 1 ,240.3   ,70,70,70
BEGIN DESCRIPTION:
RICH CNTY FEMA XS: Z
END DESCRIPTION:
#Sta/Elev= 15
     300     305     500   298.5     800     294     900   295.5    1000     297
    1000     290    1010     284    1013   284.5    1020     288    1027     288
    1027     289    1036     297    1100   296.3    1200     296    1400     302
#Mann= 3 , 0 , 0
     300     .12       0    1000     .06       0    1027     .12       0
Bank Sta=1000,1027
XS Rating Curve= 0 ,0
Exp/Cntr=0.3,0.1

Type RM Length L Ch R = 1 ,233.3   ,50,50,50
#Sta/Elev= 14
      50     285     100     284     205     284     212     282     215   280.8
     218   278.4     224   276.8     230   278.3     233   280.8     235   280.9
     240   283.9     250     284     410     284     520     290
#Mann= 3 , 0 , 0
      50     .12       0     205     .06       0     250     .12       0
Bank Sta=205,250
XS Rating Curve= 0 ,0
Exp/Cntr=0.3,0.1

Type RM Length L Ch R = 1 ,232.8   ,100,100,100
#Sta/Elev= 14
       0     285      50     284     230     284     300   283.3     312     282
     315   280.8     318   278.4     324   276.8     330   278.3     333   280.8
     335   280.9     340   283.9     395     284     590     290
#Mann= 3 , 0 , 0
       0     .12       0     300     .06       0     340     .12       0
Bank Sta=300,340
XS Rating Curve= 0 ,0
Exp/Cntr=0.3,0.1

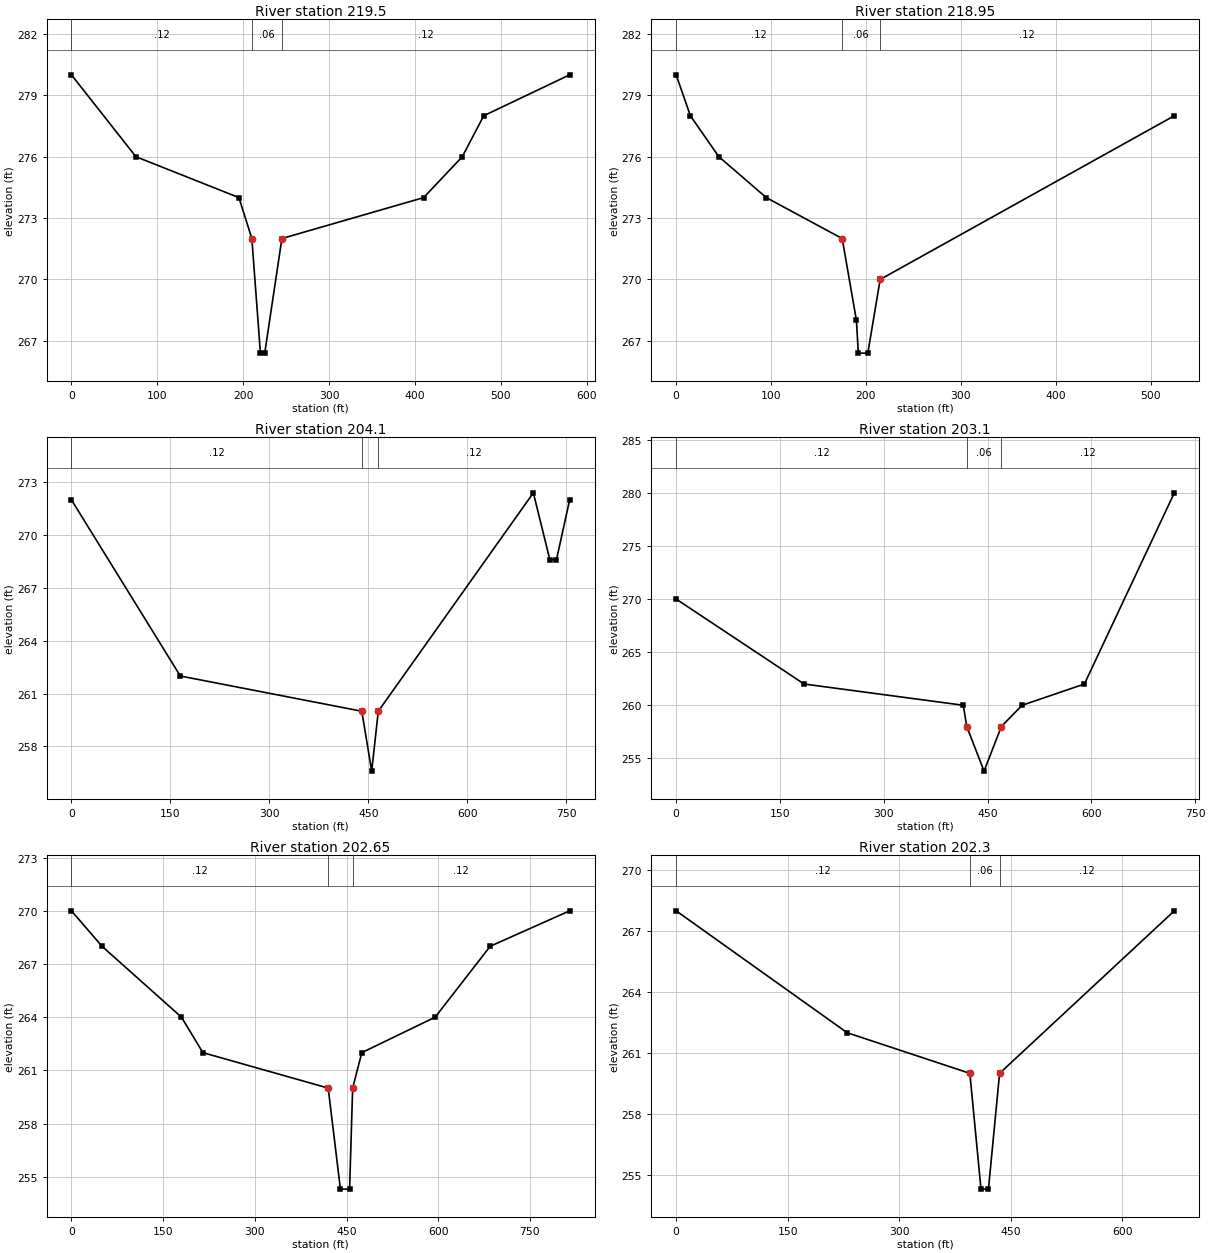
Type RM Length L Ch R = 1 ,219.5   ,55,55,55
#Sta/Elev= 11
       0     280      75     276     195     274     210     272     220   266.4
     225   266.4     245     272     410     274     455     276     480     278
     580     280
#Mann= 3 , 0 , 0
       0     .12       0     210     .06       0     245     .12       0
Bank Sta=210,245
XS Rating Curve= 0 ,0
Exp/Cntr=0.3,0.1

Type RM Length L Ch R = 1 ,218.95  ,65,65,65
#Sta/Elev= 10
       0     280      15     278      45     276      95     274     175     272
     190     268     192   266.4     202   266.4     215     270     525     278
#Mann= 3 , 0 , 0
       0     .12       0     175     .06       0     215     .12       0
Bank Sta=175,215
XS Rating Curve= 0 ,0
Exp/Cntr=0.3,0.1

Type RM Length L Ch R = 1 ,204.1   ,100,100,100
#Sta/Elev= 9
       0     272     165     262     440     260     455   256.6     465     260
     700   272.4     725   268.6     735   268.6     755     272
#Mann= 3 , 0 , 0
       0     .12       0     440     .06       0     465     .12       0
Bank Sta=440,465
XS Rating Curve= 0 ,0
Exp/Cntr=0.3,0.1

Type RM Length L Ch R = 1 ,203.1   ,15,15,15
#Sta/Elev= 9
       0     270     185     262     415     260     420     258     445   253.8
     470     258     500     260     590     262     720     280
#Mann= 3 , 0 , 0
       0     .12       0     420     .06       0     470     .12       0
Bank Sta=420,470
XS Rating Curve= 0 ,0
Exp/Cntr=0.3,0.1

Type RM Length L Ch R = 1 ,202.65  ,35,35,35
#Sta/Elev= 12
       0     270      50     268     180     264     215     262     420     260
     440   254.3     455   254.3     460     260     475     262     595     264
     685     268     815     270
#Mann= 3 , 0 , 0
       0     .12       0     420     .06       0     460     .12       0
Bank Sta=420,460
XS Rating Curve= 0 ,0
Exp/Cntr=0.3,0.1

Type RM Length L Ch R = 1 ,202.3   ,50,50,50
#Sta/Elev= 7
       0     268     230     262     395     260     410   254.3     420   254.3
     435     260     670     268
#Mann= 3 , 0 , 0
       0     .12       0     395     .06       0     435     .12       0
Bank Sta=395,435
XS Rating Curve= 0 ,0
Exp/Cntr=0.3,0.1

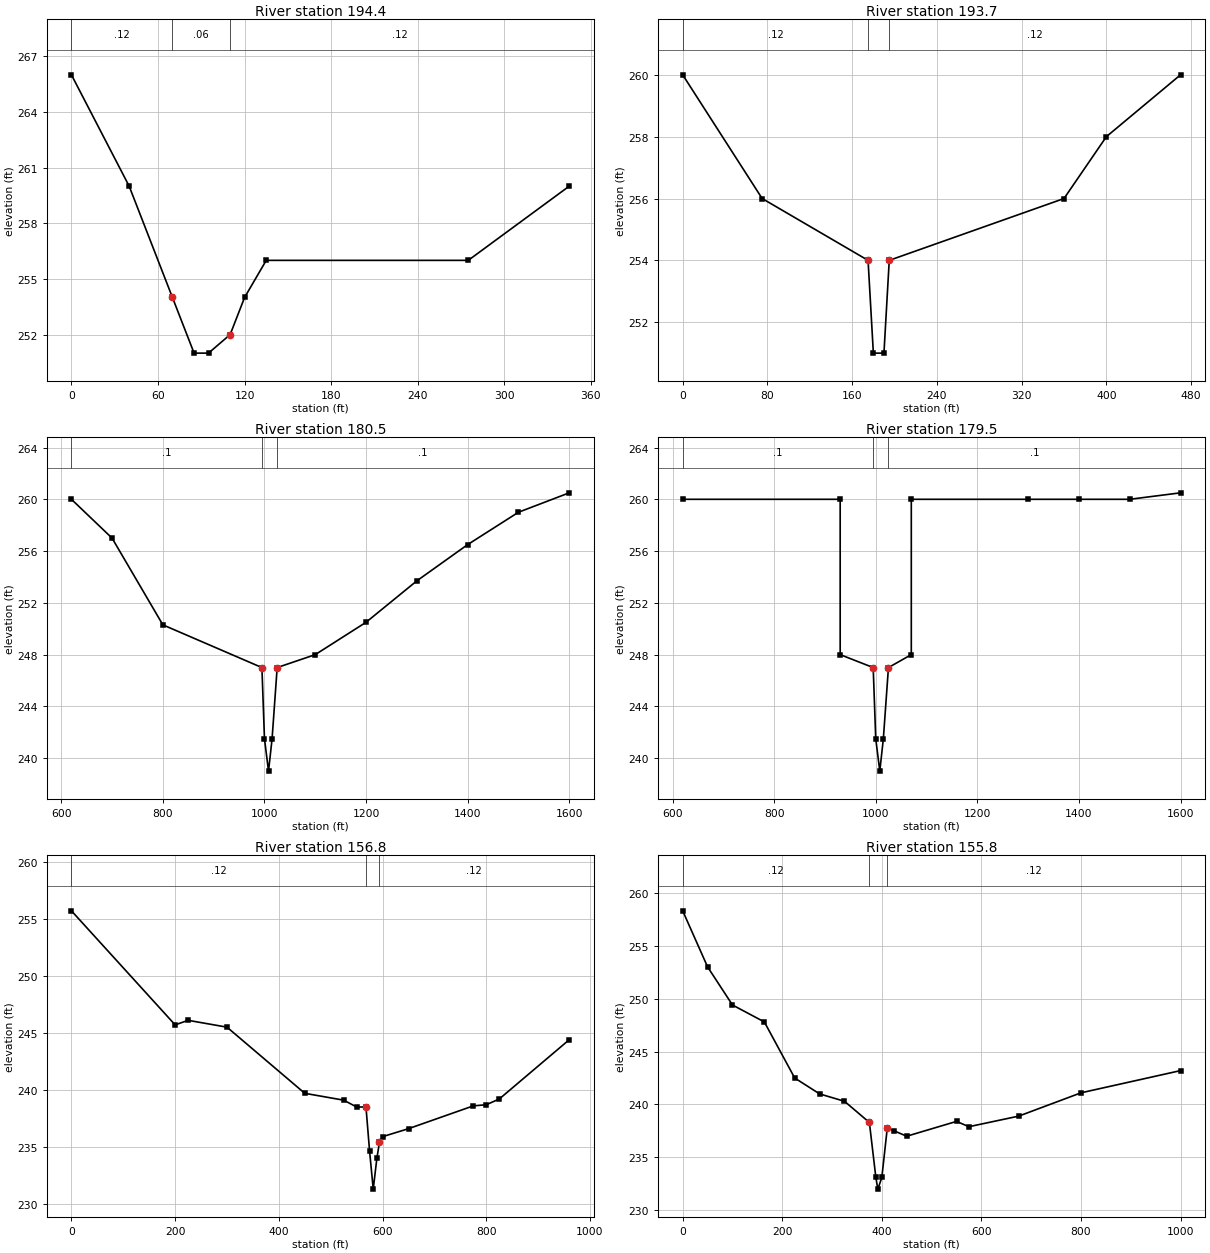
Type RM Length L Ch R = 1 ,194.4   ,70,70,60
BEGIN DESCRIPTION:
RICH CNTY FEMA XS: R
END DESCRIPTION:
#Sta/Elev= 10
       0     266      40     260      70     254      85     251      95     251
     110     252     120     254     135     256     275     256     345     260
#Mann= 3 , 0 , 0
       0     .12       0      70     .06       0     110     .12       0
Bank Sta=70,110
XS Rating Curve= 0 ,0
Exp/Cntr=0.3,0.1

Type RM Length L Ch R = 1 ,193.7   ,65,65,65
#Sta/Elev= 9
       0     260      75     256     175     254     180     251     190     251
     195     254     360     256     400     258     470     260
#Mann= 3 , 0 , 0
       0     .12       0     175     .06       0     195     .12       0
Bank Sta=175,195
XS Rating Curve= 0 ,0
Exp/Cntr=0.3,0.1

Type RM Length L Ch R = 1 ,180.5   ,100,100,100
#Sta/Elev= 14
     620     260     700     257     800   250.3     995     247    1000   241.5
    1008     239    1015   241.5    1025     247    1100     248    1200   250.5
    1300   253.7    1400   256.5    1500     259    1600   260.5
#Mann= 3 , 0 , 0
     620      .1       0     995     .06       0    1025      .1       0
Bank Sta=995,1025
XS Rating Curve= 0 ,0
Exp/Cntr=0.3,0.1

Type RM Length L Ch R = 1 ,179.5   ,50,50,50
#Sta/Elev= 14
     620     260     930     260     930     248     995     247    1000   241.5
    1008     239    1015   241.5    1025     247    1070     248    1070     260
    1300     260    1400     260    1500     260    1600   260.5
#Mann= 3 , 0 , 0
     620      .1       0     995     .06       0    1025      .1       0
Bank Sta=995,1025
XS Rating Curve= 0 ,0
Exp/Cntr=0.3,0.1

Type RM Length L Ch R = 1 ,156.8   ,100,100,100
#Sta/Elev= 18
       0   255.7     200   245.7     225   246.1     300   245.5     450   239.7
     525   239.1     550   238.5     568   238.5     575   234.6     582   231.3
     589     234     594   235.4     600   235.9     650   236.6     775   238.6
     800   238.7     825   239.2     960   244.4
#Mann= 3 , 0 , 0
       0     .12       0     568     .06       0     594     .12       0
Bank Sta=568,594
XS Rating Curve= 0 ,0
Exp/Cntr=0.3,0.1

Type RM Length L Ch R = 1 ,155.8   ,20,20,20
#Sta/Elev= 19
       0   258.3      50     253     100   249.4     164   247.8     225   242.5
     275     241     325   240.3     375   238.3     388   233.1     392     232
     400   233.1     411   237.8     425   237.5     450     237     550   238.4
     575   237.9     675   238.9     800   241.1    1000   243.2
#Mann= 3 , 0 , 0
       0     .12       0     375     .06       0     411     .12       0
Bank Sta=375,411
XS Rating Curve= 0 ,0
Exp/Cntr=0.3,0.1

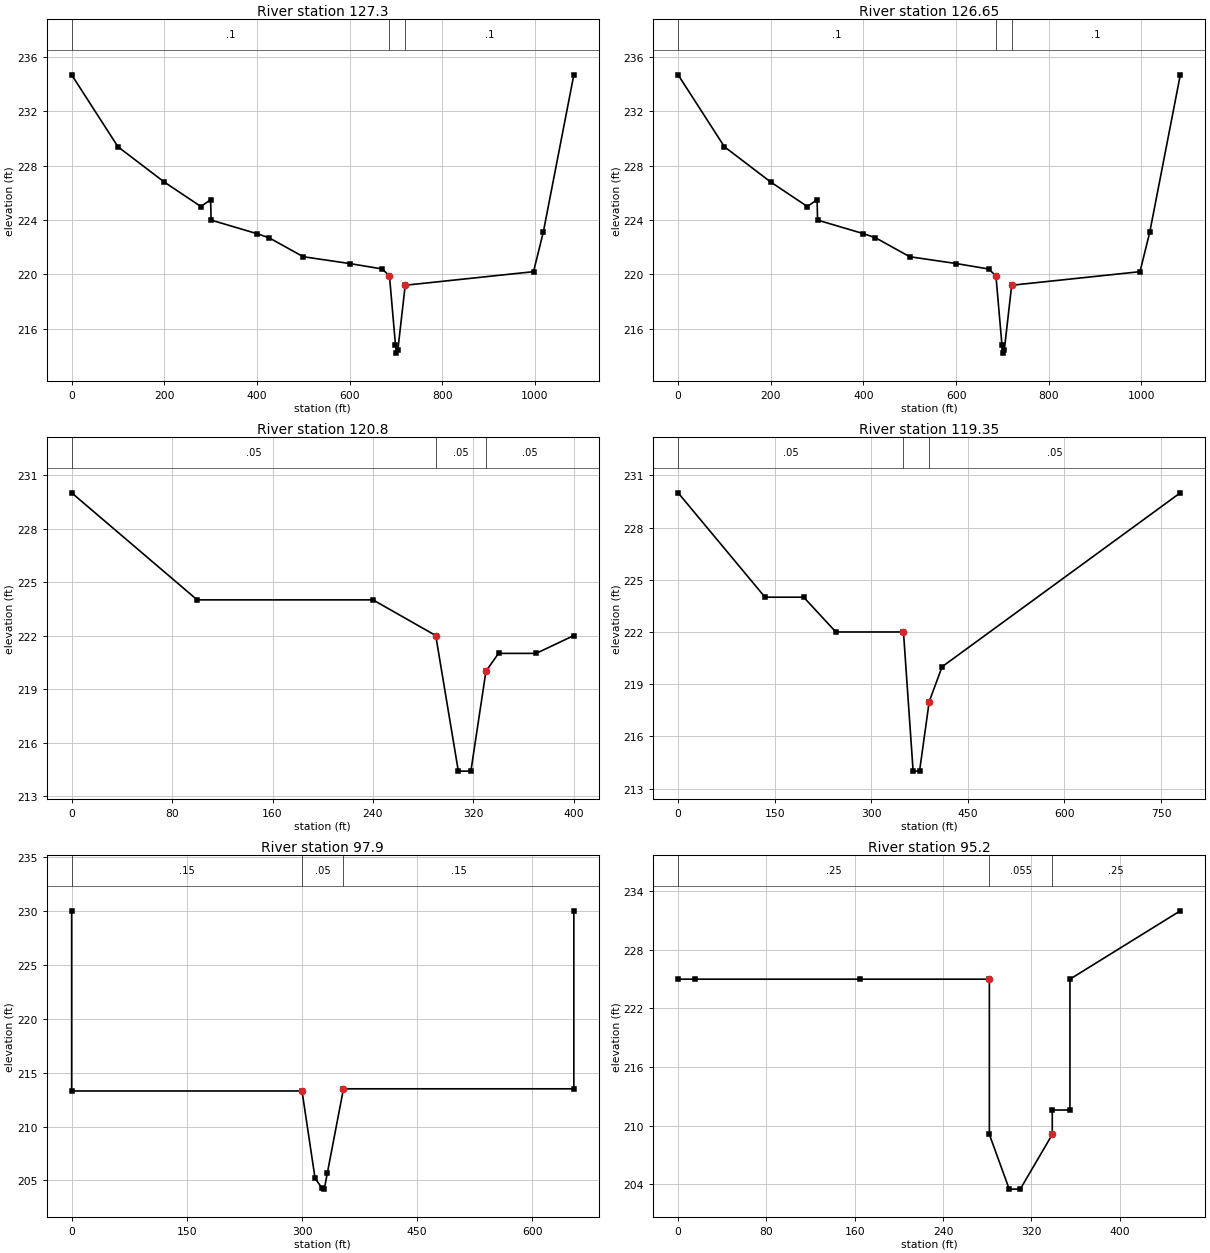
Type RM Length L Ch R = 1 ,127.3   ,65,65,65
#Sta/Elev= 19
       0   234.7     100   229.4     200   226.8     279     225     300   225.5
     301     224     400     223     426   222.7     500   221.3     600   220.8
     670   220.4     686   219.9     699   214.8     701   214.2     704   214.4
     720   219.2     997   220.2    1018   223.1    1084   234.7
#Mann= 3 , 0 , 0
       0      .1       0     686     .06       0     720      .1       0
Bank Sta=686,720
XS Rating Curve= 0 ,0
Exp/Cntr=0.3,0.1

Type RM Length L Ch R = 1 ,126.65  ,25,25,25
BEGIN DESCRIPTION:
RICH CNTY FEMA XS: G
END DESCRIPTION:
#Sta/Elev= 19
       0   234.7     100   229.4     200   226.8     279     225     300   225.5
     301     224     400     223     426   222.7     500   221.3     600   220.8
     670   220.4     686   219.9     699   214.8     701   214.2     704   214.4
     720   219.2     997   220.2    1018   223.1    1084   234.7
#Mann= 3 , 0 , 0
       0      .1       0     686     .06       0     720      .1       0
Bank Sta=686,720
XS Rating Curve= 0 ,0
Exp/Cntr=0.3,0.1

Type RM Length L Ch R = 1 ,120.8   ,145,145,145
BEGIN DESCRIPTION:
RICH CNTY FEMA XS: F
END DESCRIPTION:
#Sta/Elev= 10
       0     230     100     224     240     224     290     222     308   214.4
     318   214.4     330     220     340     221     370     221     400     222
#Mann= 3 , 0 , 0
       0     .05       0     290     .05       0     330     .05       0
Bank Sta=290,330
XS Rating Curve= 0 ,0
Exp/Cntr=0.4,0.2

Type RM Length L Ch R = 1 ,119.35  ,80,80,80
#Sta/Elev= 10
       0     230     135     224     195     224     245     222     350     222
     365     214     375     214     390     218     410     220     780     230
#Mann= 3 , 0 , 0
       0     .05       0     350     .05       0     390     .05       0
Bank Sta=350,390
XS Rating Curve= 0 ,0
Exp/Cntr=0.4,0.2

Type RM Length L Ch R = 1 ,97.9    ,60,60,60
#Sta/Elev= 10
       0     230       0   213.3     300   213.3     317   205.2     326   204.3
     329   204.2     333   205.7     354   213.5     654   213.5     654     230
#Mann= 3 , 0 , 0
       0     .15       0     300     .05       0     354     .15       0
Bank Sta=300,354
XS Rating Curve= 0 ,0
Exp/Cntr=0.5,0.3

Type RM Length L Ch R = 1 ,95.2    ,40,40,40
#Sta/Elev= 12
       0     225      15     225     165     225     282     225     282   209.1
     300   203.5     310   203.5     339   209.1     339   211.6     355   211.6
     355     225     455     232
#Mann= 3 , 0 , 0
       0     .25       0     282    .055       0     339     .25       0
Bank Sta=282,339
XS Rating Curve= 0 ,0
Exp/Cntr=0.5,0.3