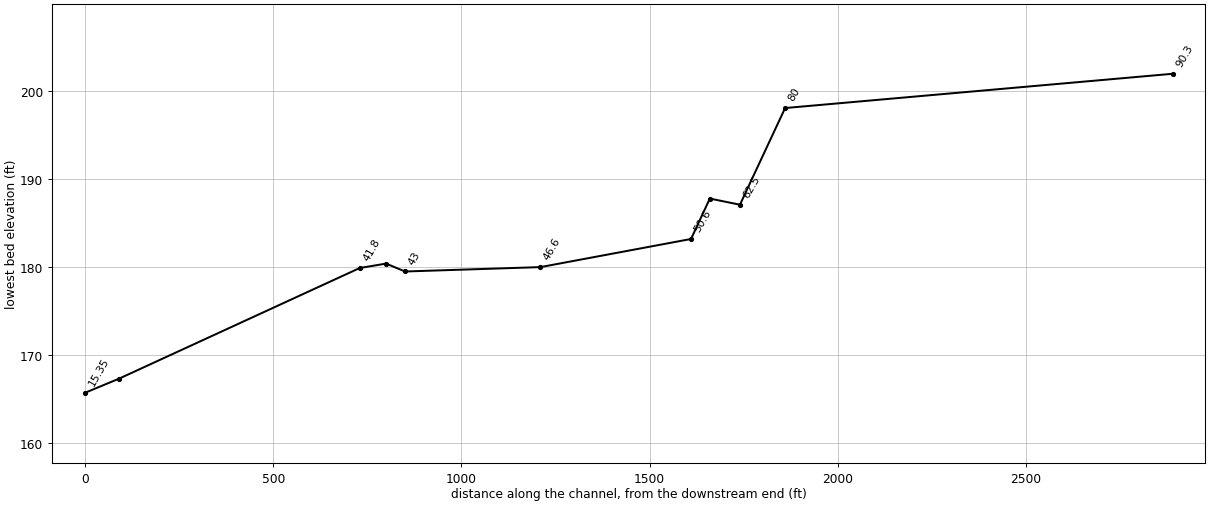
HEC-RAS study CCR_Stoop.prj: CCR_Stoop

--- CCR_Stoop.g02 (geometry) --- (continued)

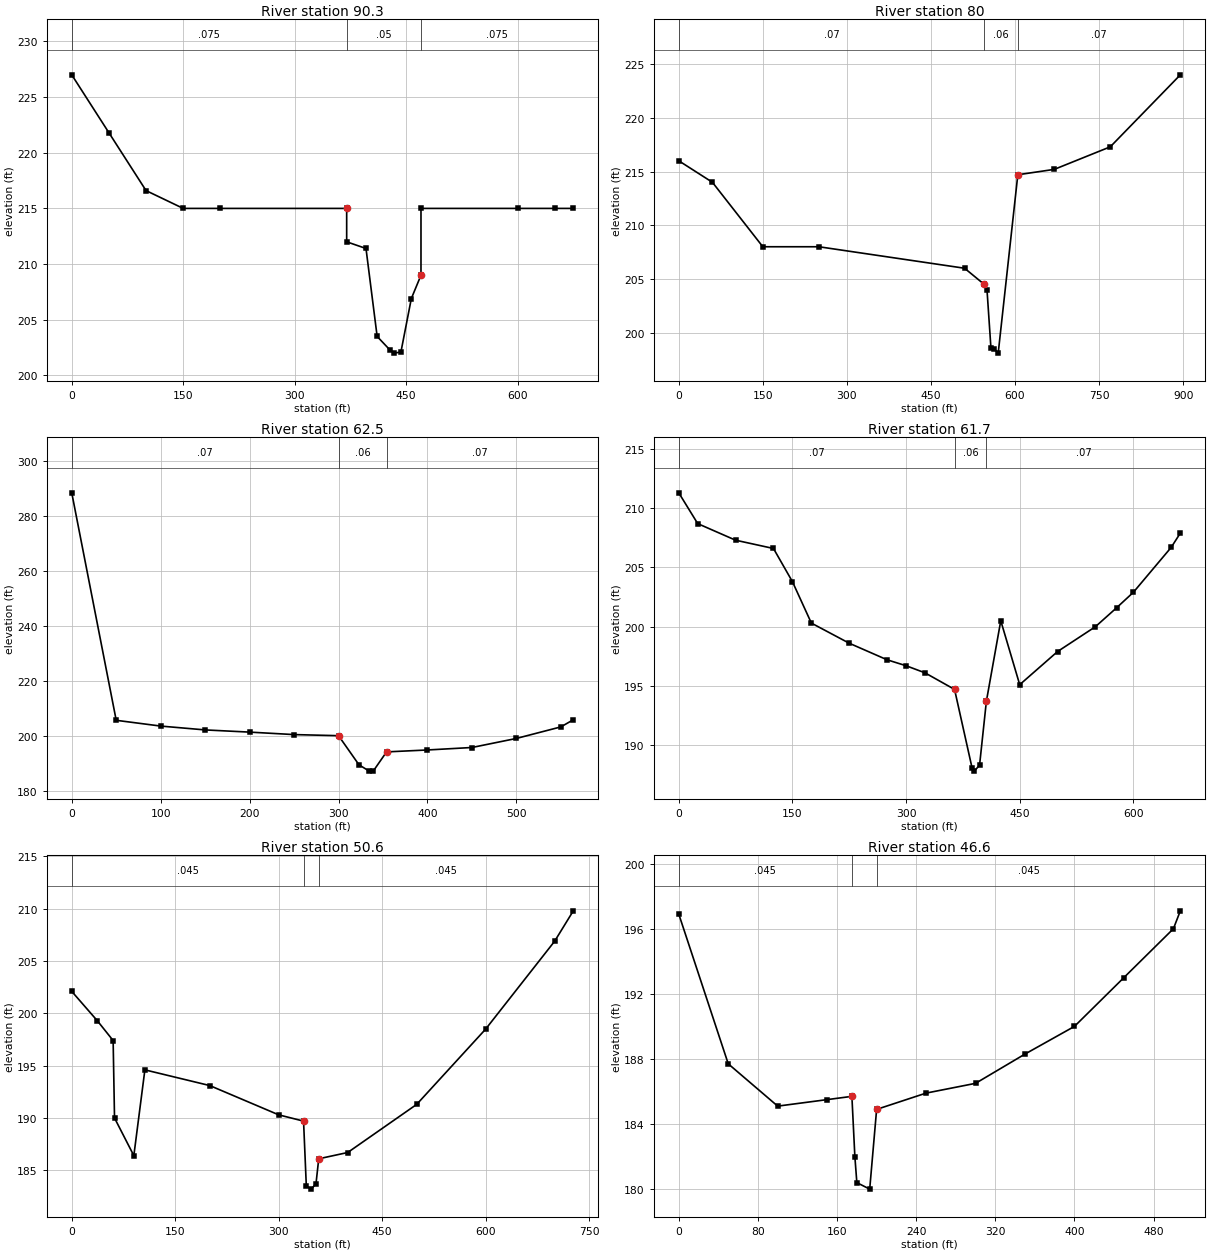
Type RM Length L Ch R = 1 ,90.3    ,1030,1030,1030
#Sta/Elev= 18
       0     227      50   221.8     100   216.6     150     215     200     215
     370     215     370     212     396   211.4     411   203.5     428   202.3
     434     202     443   202.1     457   206.9     470     209     470     215
     600     215     650     215     675     215
#Mann= 3 , 0 , 0
       0    .075       0     370     .05       0     470    .075       0
Bank Sta=370,470
XS Rating Curve= 0 ,0
Exp/Cntr=0.5,0.3

Type RM Length L Ch R = 1 ,80      ,120,120,120
BEGIN DESCRIPTION:
LEX CNTY FEMA XS: N
END DESCRIPTION:
#Sta/Elev= 14
       0     216      60     214     150     208     250     208     510     206
     545   204.5     550     204     557   198.6     563   198.5     570   198.1
     605   214.7     670   215.2     770   217.3     895     224
#Mann= 3 , 0 , 0
       0     .07       0     545     .06       0     605     .07       0
Bank Sta=545,605
XS Rating Curve= 0 ,0
Exp/Cntr=0.5,0.1

Type RM Length L Ch R = 1 ,62.5    ,80,80,80
#Sta/Elev= 16
       0   288.4      50   205.6     100   203.5     150   202.1     200   201.3
     250   200.4     300     200     323   189.4     334   187.2     339   187.1
     354   194.1     400   194.8     450   195.7     500     199     550   203.2
     564   205.8
#Mann= 3 , 0 , 0
       0     .07       0     300     .06       0     354     .07       0
Bank Sta=300,354
XS Rating Curve= 0 ,0
Exp/Cntr=0.3,0.1

Type RM Length L Ch R = 1 ,61.7    ,50,50,50
#Sta/Elev= 23
       0   211.3      25   208.7      75   207.3     125   206.6     150   203.8
     175   200.3     225   198.6     275   197.2     300   196.7     325   196.1
     364   194.7     387   188.1     390   187.8     397   188.3     406   193.7
     425   200.5     450   195.1     500   197.9     550     200     578   201.6
     600   202.9     650   206.7     662   207.9
#Mann= 3 , 0 , 0
       0     .07       0     364     .06       0     406     .07       0
Bank Sta=364,406
XS Rating Curve= 0 ,0
Exp/Cntr=0.3,0.1

Type RM Length L Ch R = 1 ,50.6    ,400,400,400
#Sta/Elev= 18
       0   202.1      37   199.3      60   197.4      62     190      90   186.4
     106   194.6     200   193.1     300   190.3     336   189.7     340   183.5
     347   183.2     354   183.7     358   186.1     400   186.7     500   191.3
     600   198.5     700   206.9     727   209.8
#Mann= 3 , 0 , 0
       0    .045       0     336   .0315       0     358    .045       0
Bank Sta=336,358
XS Rating Curve= 0 ,0
Exp/Cntr=0.3,0.1

Type RM Length L Ch R = 1 ,46.6    ,360,360,360
BEGIN DESCRIPTION:
LEX CNTY FEMA XS: H
END DESCRIPTION:
#Sta/Elev= 16
       0   196.9      50   187.7     100   185.1     150   185.5     175   185.7
     178     182     180   180.4     193     180     200   184.9     250   185.9
     300   186.5     350   188.3     400     190     450     193     500     196
     507   197.1
#Mann= 3 , 0 , 0
       0    .045       0     175   .0315       0     200    .045       0
Bank Sta=175,200
XS Rating Curve= 0 ,0
Exp/Cntr=0.5,0.3

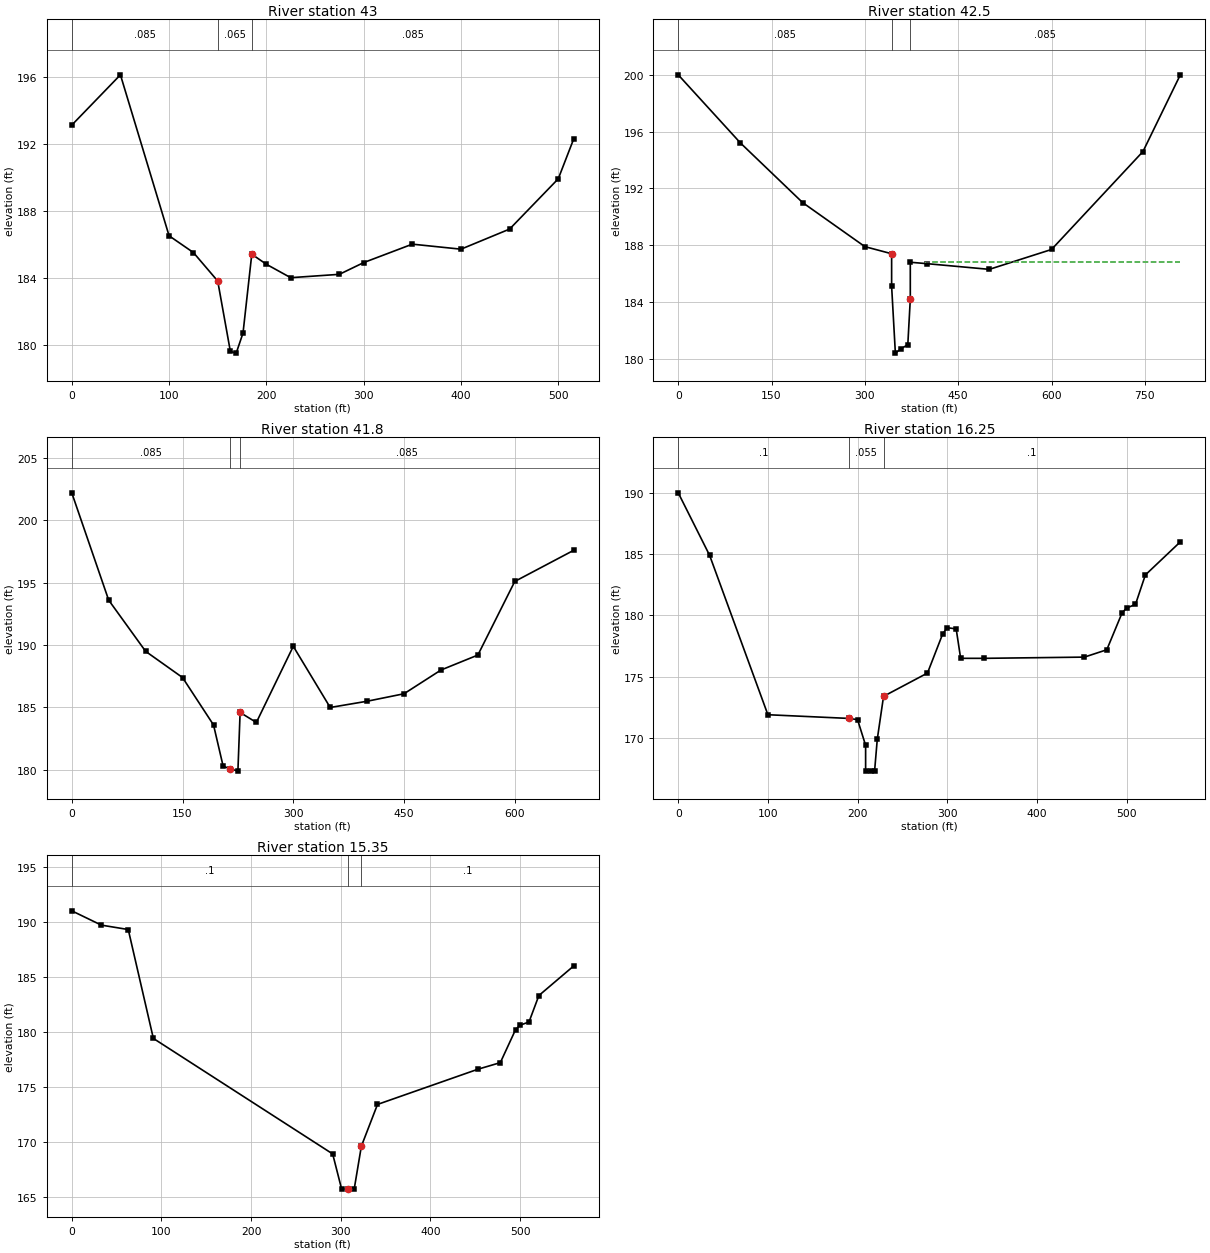
Type RM Length L Ch R = 1 ,43      ,50,50,50
BEGIN DESCRIPTION:
LEX CNTY FEMA XS: G
END DESCRIPTION:
#Sta/Elev= 18
       0   193.1      50   196.1     100   186.5     125   185.5     150   183.8
     163   179.6     169   179.5     176   180.7     185   185.4     200   184.8
     225     184     275   184.2     300   184.9     350     186     400   185.7
     450   186.9     500   189.9     516   192.3
#Mann= 3 , 0 , 0
       0    .085       0     150    .065       0     185    .085       0
Bank Sta=150,185
XS Rating Curve= 0 ,0
Exp/Cntr=0.3,0.1

Type RM Length L Ch R = 1 ,42.5    ,70,70,70
BEGIN DESCRIPTION:
LEX CNTY FEMA XS: F
END DESCRIPTION:
#Sta/Elev= 16
       0     200     100   195.2     200     191     300   187.9     343   187.4
     343   185.1     349   180.4     358   180.7     369     181     373   184.2
     373   186.8     400   186.7     500   186.3     600   187.7     747   194.6
     807     200
#Mann= 3 , 0 , 0
       0    .085       0     343    .065       0     373    .085       0
#XS Ineff= 2 , 0
       0   335.5   186.8   396.5       0   186.8
Permanent Ineff=
       F       F
Bank Sta=343,373
XS Rating Curve= 0 ,0
Exp/Cntr=0.3,0.1

Type RM Length L Ch R = 1 ,41.8    ,640,640,640
#Sta/Elev= 18
       0   202.2      50   193.6     100   189.5     150   187.4     192   183.6
     205   180.3     214   180.1     225   179.9     228   184.6     250   183.8
     300   189.9     350     185     400   185.5     450   186.1     500     188
     550   189.2     600   195.1     680   197.6
#Mann= 3 , 0 , 0
       0    .085       0     214    .055       0     228    .085       0
Bank Sta=214,228
XS Rating Curve= 0 ,0
Exp/Cntr=0.3,0.1

Type RM Length L Ch R = 1 ,16.25   ,90,90,90
#Sta/Elev= 24
       0     190      35   184.9     100   171.9     190   171.6     200   171.5
     209   169.4     209   167.3     215   167.3     219   167.3     222   169.9
     229   173.4     278   175.3     295   178.5     300     179     310   178.9
     315   176.5     341   176.5     453   176.6     478   177.2     495   180.2
     500   180.6     510   180.9     521   183.3     560     186
#Mann= 3 , 0 , 0
       0      .1       0     190    .055       0     229      .1       0
Bank Sta=190,229
XS Rating Curve= 0 ,0
Exp/Cntr=0.3,0.1

Type RM Length L Ch R = 1 ,15.35   ,45,45,45
#Sta/Elev= 17
       0     191      33   189.7      63   189.3      91   179.4     291   168.9
     301   165.7     308   165.7     315   165.7     323   169.6     341   173.4
     453   176.6     478   177.2     495   180.2     500   180.6     510   180.9
     521   183.3     560     186
#Mann= 3 , 0 , 0
       0      .1       0     308    .055       0     323      .1       0
Bank Sta=308,323
XS Rating Curve= 0 ,0
Exp/Cntr=0.3,0.1

--- CCR_Stoop.g03 (geometry) ---

Geom Title=Corrected
Program Version=4.10
BEGIN GEOM DESCRIPTION:
Lexington County portion of the model corrected.  Anticipate updated Richland County model.  Will combine once received.
END GEOM DESCRIPTION:

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
River Reach=Stoop Creek     ,Stoop Creek

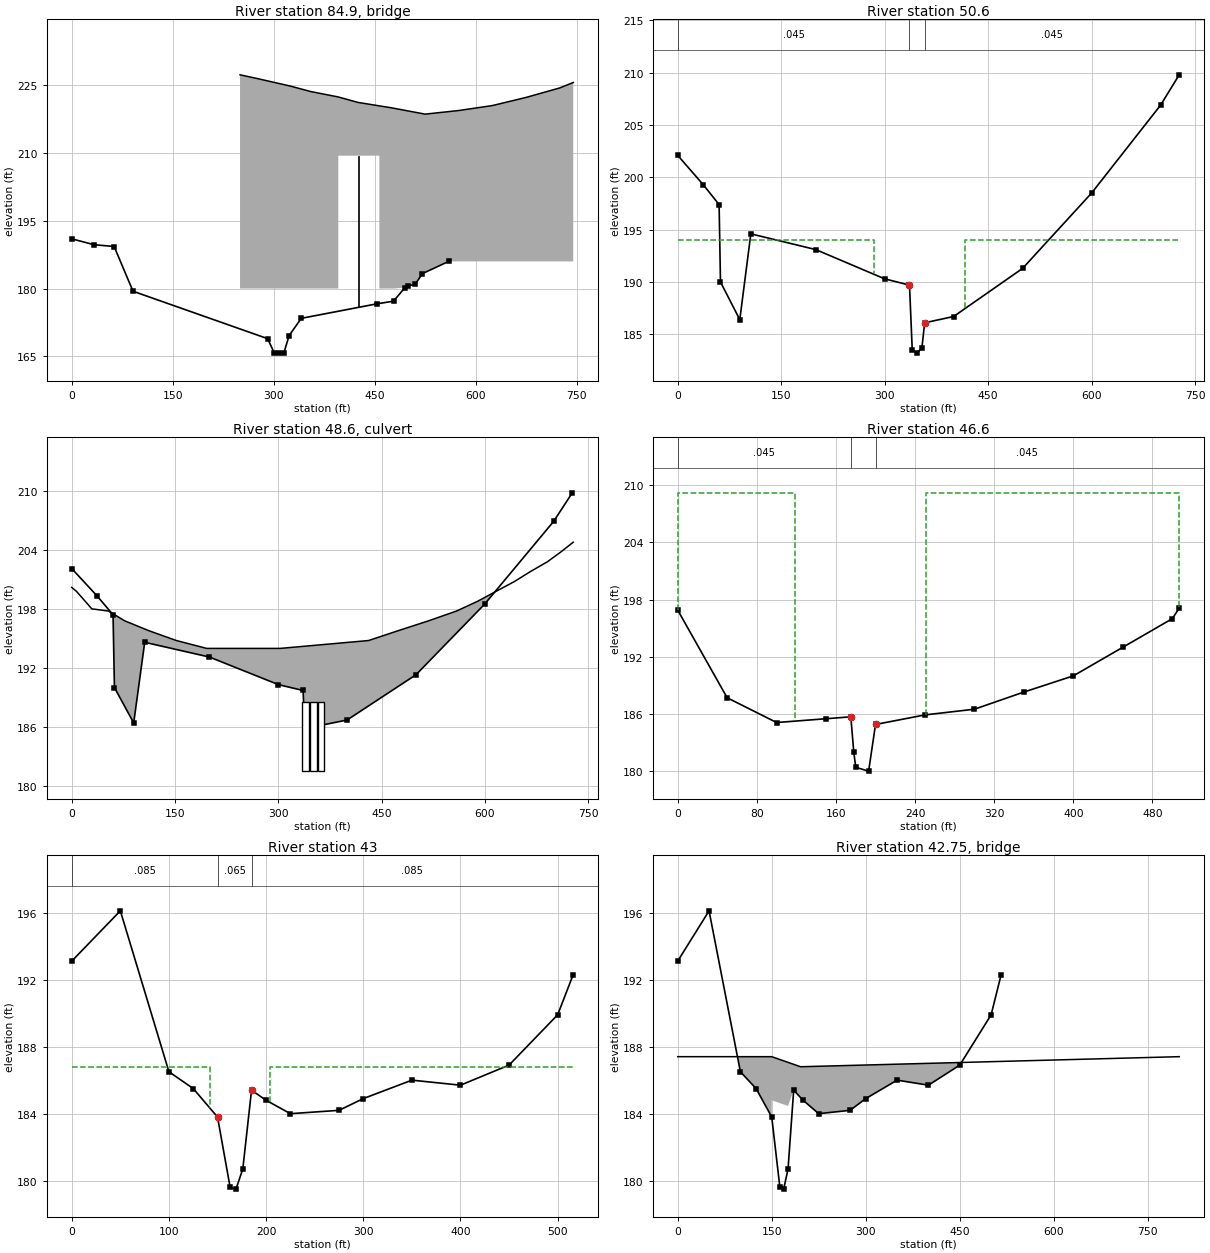
Type RM Length L Ch R = 3 ,84.9    ,,,
BEGIN DESCRIPTION:
Bridge #5 - Frontage Road, I-26 Ramps & Fernandina Rd.
END DESCRIPTION:
Bridge Culvert--1,0,-1,-1, 0
Deck Dist Width WeirC Skew NumUp NumDn MinLoCord MaxHiCord MaxSubmerge Is_Ogee
0.25,979.5,2.8,0, 16, 17, 218.6, , 0.98, 0, 0,0,,
     250     275     325     355     396     396     425     457     457     475
     525     575     625     675     725     745
   227.3   226.5   224.8   223.6   222.4   222.4   221.2  220.43  220.43     220
   218.6   219.4   220.5   222.3   224.4   225.6
     180     180     180     180     180   209.4   209.4   209.4     180     180
     180     180     180     180     180     180
     250     275     325     355     395     425     475     525     545     545
     575     605     605     625     675     725     745
   227.3   226.5   224.8   223.6   222.4   221.2     220   218.6  218.92  218.92
   219.4  220.06  220.06   220.5   222.3   224.4   225.6
     180     180     180     180     180     180     180     180     180   209.4
   209.4   209.4     180     180     180     180     180
Pier Skew, UpSta & Num, DnSta & Num=  ,426.5, 2 ,575, 2 , 0 , 0 , 0 ,,
       1       1
     202   209.4
       1       1
   198.1   209.4
BR Coef= 0 , 0 ,-1 ,1.25, 0 ,,,0.5504819,0,,2,209.4
WSPro=,,,, 1 ,,,, 0 ,,,, 0 ,,,,-1 ,-1 ,-1 , 0 , 0 , 0 , 0 , 0
BC Design=,, 0 ,, 0 ,,,,,,
BC Use User HTab Curves=0
BC User HTab FreeFlow(D)= 0

Type RM Length L Ch R = 1 ,50.6    ,400,400,400
#Sta/Elev= 18
       0   202.1      37   199.3      60   197.4      62     190      90   186.4
     106   194.6     200   193.1     300   190.3     336   189.7     340   183.5
     347   183.2     354   183.7     358   186.1     400   186.7     500   191.3
     600   198.5     700   206.9     727   209.8
#Mann= 3 , 0 , 0
       0    .045       0     336   .0315       0     358    .045       0
#XS Ineff= 2 , 0
       0     285  193.98     417       0  193.98
Permanent Ineff=
       F       F
Bank Sta=336,358
XS Rating Curve= 0 ,0
Exp/Cntr=0.5,0.3

Type RM Length L Ch R = 2 ,48.6    ,,,
BEGIN DESCRIPTION:
I-20 - Note: Upstream Deck/Roadwy information is for Berryhill Drive.  Downstream Deck/Roadway information is I-20 EB EOP.  I-20 WB elevations are approximately 213-214 in NAVD88.  Culvert inverts assumed based on Aerial Mapping of existing contours.
END DESCRIPTION:
Bridge Culvert--1,0,-1,-1, 0
Deck Dist Width WeirC Skew NumUp NumDn MinLoCord MaxHiCord MaxSubmerge Is_Ogee
95,210,2.6,0, 20, 7, , , 0.98, 0, 0,0,,
       0     6.9    29.2    53.2    77.1     112     152     196   302.8   431.1
   474.1   518.1   558.9   589.8   616.2     643   665.9   690.7   710.3   728.4
  200.18  199.78     198  197.78  196.78  195.78  194.78  193.98  193.98  194.78
  195.78  196.78  197.78  198.78  199.78  200.78  201.78  202.78  203.78  204.78
                                                                                
                                                                                
       0      24    85.4     151   266.4   424.6     508
  211.98  211.78  210.78  209.78  209.21  209.78  210.28
                                                        
BR Coef=-1 , 0 , 0 ,, 0 ,,,0.8,-1,,0,
WSPro=,,,, 1 ,,,, 0 ,,,, 0 ,,,,-1 ,-1 ,-1 , 0 , 0 , 0 , 0 , 0
Multiple Barrel Culv=2,7,10,300,0.012,0.2,1,8,1,181.5,179.8, 3,Culvert #1  , 0 ,50
     340     174     351     185     362     196
Culvert Bottom n=0.012
BC Design=,, 0 ,, 0 ,,,,,,
BC Use User HTab Curves=0
BC User HTab FreeFlow(D)= 0

Type RM Length L Ch R = 1 ,46.6    ,360,360,360
BEGIN DESCRIPTION:
LEX CNTY FEMA XS: H
END DESCRIPTION:
#Sta/Elev= 16
       0   196.9      50   187.7     100   185.1     150   185.5     175   185.7
     178     182     180   180.4     193     180     200   184.9     250   185.9
     300   186.5     350   188.3     400     190     450     193     500     196
     507   197.1
#Mann= 3 , 0 , 0
       0    .045       0     175   .0315       0     200    .045       0
#XS Ineff= 2 , 0
       0     119  209.21     251       0  209.21
Permanent Ineff=
       F       F
Bank Sta=175,200
XS Rating Curve= 0 ,0
Exp/Cntr=0.5,0.3

Type RM Length L Ch R = 1 ,43      ,50,50,50
BEGIN DESCRIPTION:
LEX CNTY FEMA XS: G
END DESCRIPTION:
#Sta/Elev= 18
       0   193.1      50   196.1     100   186.5     125   185.5     150   183.8
     163   179.6     169   179.5     176   180.7     185   185.4     200   184.8
     225     184     275   184.2     300   184.9     350     186     400   185.7
     450   186.9     500   189.9     516   192.3
#Mann= 3 , 0 , 0
       0    .085       0     150    .065       0     185    .085       0
#XS Ineff= 2 , 0
       0   142.5   186.8   203.5       0   186.8
Permanent Ineff=
       F       F
Bank Sta=150,185
XS Rating Curve= 0 ,0
Exp/Cntr=0.5,0.3

Type RM Length L Ch R = 3 ,42.75   ,,,
BEGIN DESCRIPTION:
Rockland Road Bridge (S-1241) based on SCDOT Roadway Plans File No. 32.595 (1973)
END DESCRIPTION:
Bridge Culvert--1,0,-1,-1, 0
Deck Dist Width WeirC Skew NumUp NumDn MinLoCord MaxHiCord MaxSubmerge Is_Ogee
7.5,35,2.6,0, 4, 4, , , 0.98, 0, 0,0,,
       0     150     196     800
   187.4   187.4   186.8   187.4
           184.8   184.2
       0     343     389     800
   187.4   187.4   186.8   187.4
           184.8   184.2
BR Coef=-1 , 0 , 0 ,, 0 ,,,0.8,-1,,0,
WSPro=,,,, 1 ,,,, 0 ,,,, 0 ,,,,-1 ,-1 ,-1 , 0 , 0 , 0 , 0 , 0
BC Design=,, 0 ,, 0 ,,,,,,
BC Use User HTab Curves=0
BC User HTab FreeFlow(D)= 0

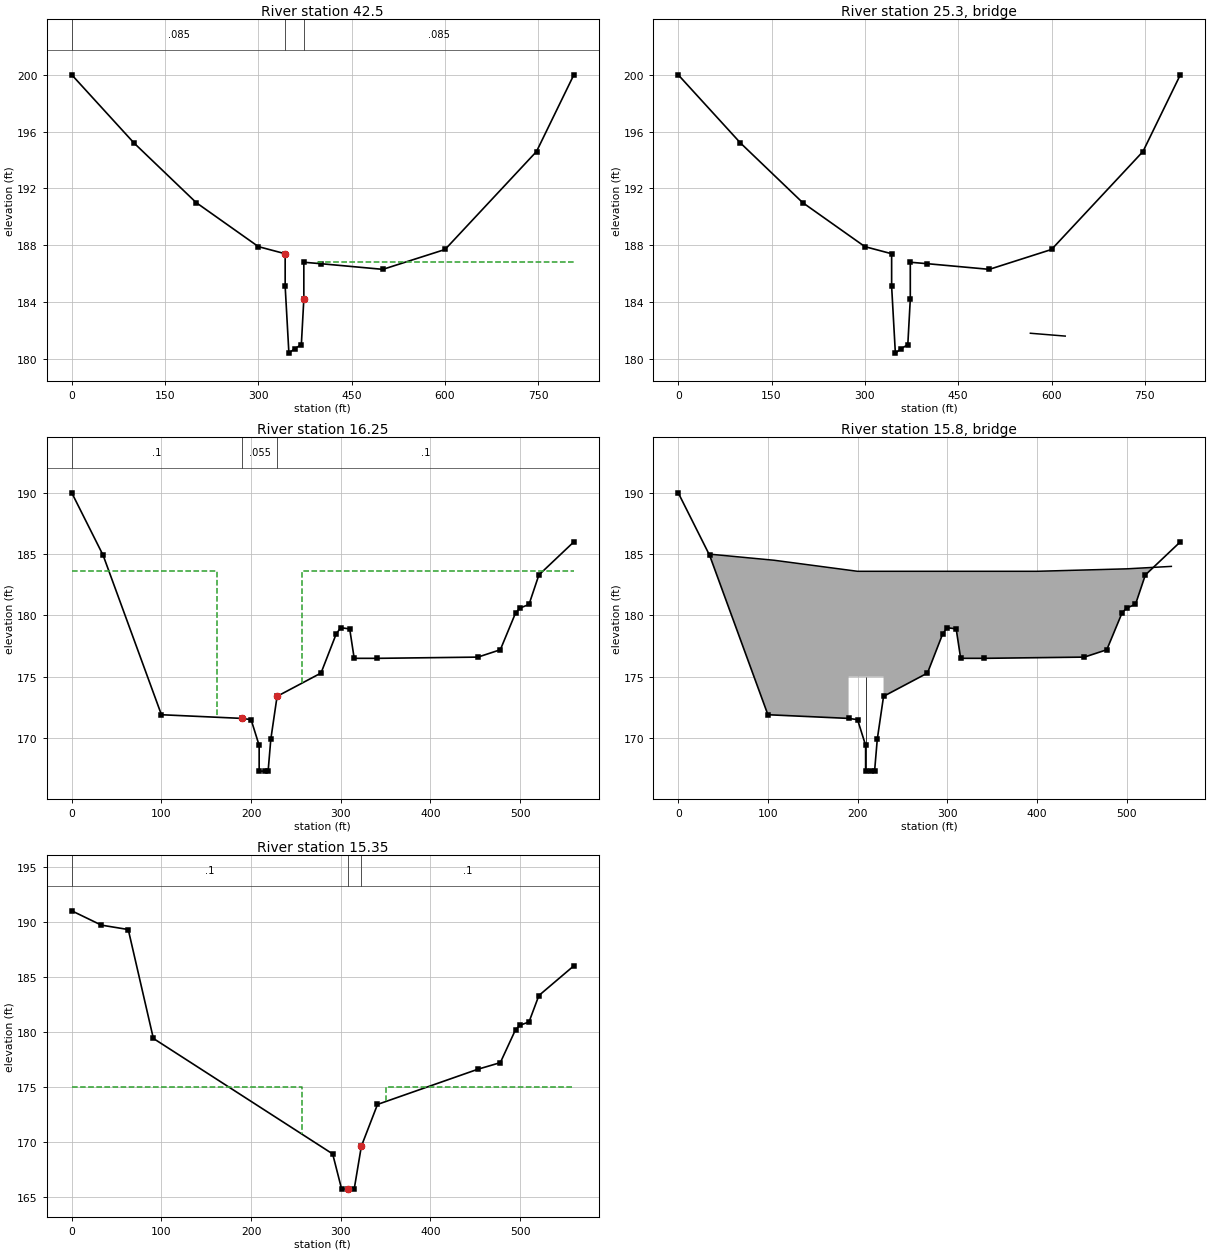
Type RM Length L Ch R = 1 ,42.5    ,70,70,70
BEGIN DESCRIPTION:
LEX CNTY FEMA XS: F
END DESCRIPTION:
#Sta/Elev= 16
       0     200     100   195.2     200     191     300   187.9     343   187.4
     343   185.1     349   180.4     358   180.7     369     181     373   184.2
     373   186.8     400   186.7     500   186.3     600   187.7     747   194.6
     807     200
#Mann= 3 , 0 , 0
       0    .085       0     343    .065       0     373    .085       0
#XS Ineff= 2 , 0
       0   335.5   186.8   396.5       0   186.8
Permanent Ineff=
       F       F
Bank Sta=343,373
XS Rating Curve= 0 ,0
Exp/Cntr=0.5,0.3

Type RM Length L Ch R = 3 ,25.3    ,,,
BEGIN DESCRIPTION:
Bridge #2 - Bush River Road Based on SCDOT Plans Project M-5010(17) Docket No. 3840.440
END DESCRIPTION:
Bridge Culvert--1,0,-1,-1, 0
Deck Dist Width WeirC Skew NumUp NumDn MinLoCord MaxHiCord MaxSubmerge Is_Ogee
0.25,89.5,2.6,0, 2, 2, , , 0.98, 0, 0,0,,
     566     622
   181.8   181.6
   180.2   180.2
     566     622
   181.8   181.6
   180.2   180.2
Pier Skew, UpSta & Num, DnSta & Num=  ,580.5, 2 ,580.5, 2 , 0 , 0 , 0 ,,
       1       1
     170   180.2
       1       1
     170   180.2
Pier Skew, UpSta & Num, DnSta & Num=  ,593.5, 2 ,593.5, 2 , 0 , 0 , 0 ,,
       1       1
     170   180.2
       1       1
     170   180.2
Pier Skew, UpSta & Num, DnSta & Num=  ,608.5, 2 ,608.5, 2 , 0 , 0 , 0 ,,
       1       1
     170   180.2
       1       1
     170   180.2
BR Coef=-1 , 0 , 0 ,, 0 ,,,0.8,-1,,1,
WSPro=,,,, 1 ,,,, 0 ,,,, 0 ,,,,-1 ,-1 ,-1 , 0 , 0 , 0 , 0 , 0
BC Design=,, 0 ,, 0 ,,,,,,
BC Use User HTab Curves=0
BC User HTab FreeFlow(D)= 0

Type RM Length L Ch R = 1 ,16.25   ,90,90,90
#Sta/Elev= 24
       0     190      35   184.9     100   171.9     190   171.6     200   171.5
     209   169.4     209   167.3     215   167.3     219   167.3     222   169.9
     229   173.4     278   175.3     295   178.5     300     179     310   178.9
     315   176.5     341   176.5     453   176.6     478   177.2     495   180.2
     500   180.6     510   180.9     521   183.3     560     186
#Mann= 3 , 0 , 0
       0      .1       0     190    .055       0     229      .1       0
#XS Ineff= 2 , 0
       0   162.5   183.6   256.5       0   183.6
Permanent Ineff=
       F       F
Bank Sta=190,229
XS Rating Curve= 0 ,0
Exp/Cntr=0.5,0.3

Type RM Length L Ch R = 3 ,15.8    ,,,
BEGIN DESCRIPTION:
Bridge #1- Railroad Bridge
END DESCRIPTION:
Bridge Culvert--1,0,-1,-1, 0
Deck Dist Width WeirC Skew NumUp NumDn MinLoCord MaxHiCord MaxSubmerge Is_Ogee
27.5,35,2.8,0, 10, 10, 183.6, , 0.98, 0, 0,0,,
      35     107     190     190     200     229     229     400     500     550
     185   184.5 183.697 183.697   183.6   183.6   183.6   183.6   183.8     184
           165.7   165.7     175     175     175   165.7   165.7   165.7   165.7
      75     107     200     284     284     323     323     400     500     550
     185   184.5   183.6   183.6   183.6   183.6   183.6   183.6   183.8     184
           165.7   165.7   165.7     175     175   165.7   165.7   165.7   165.7
Pier Skew, UpSta & Num, DnSta & Num=  ,209.5, 2 ,303.5, 2 , 0 , 0 , 0 ,,
     .01     .01
   167.3     175
     .01     .01
   165.7     175
BR Coef= 0 , 0 ,-1 ,1.5, 0 ,,,0.8873565,0,,2,175
WSPro=,,,, 1 ,,,, 0 ,,,, 0 ,,,,-1 ,-1 ,-1 , 0 , 0 , 0 , 0 , 0
BC Design=,, 0 ,, 0 ,,,,,,
BC Use User HTab Curves=0
BC User HTab FreeFlow(D)= 0

Type RM Length L Ch R = 1 ,15.35   ,45,45,45
#Sta/Elev= 17
       0     191      33   189.7      63   189.3      91   179.4     291   168.9
     301   165.7     308   165.7     315   165.7     323   169.6     341   173.4
     453   176.6     478   177.2     495   180.2     500   180.6     510   180.9
     521   183.3     560     186
#Mann= 3 , 0 , 0
       0      .1       0     308    .055       0     323      .1       0
#XS Ineff= 2 , 0
       0   256.5     175   350.5       0     175
Permanent Ineff=
       F       F
Bank Sta=308,323
XS Rating Curve= 0 ,0
Exp/Cntr=0.5,0.3